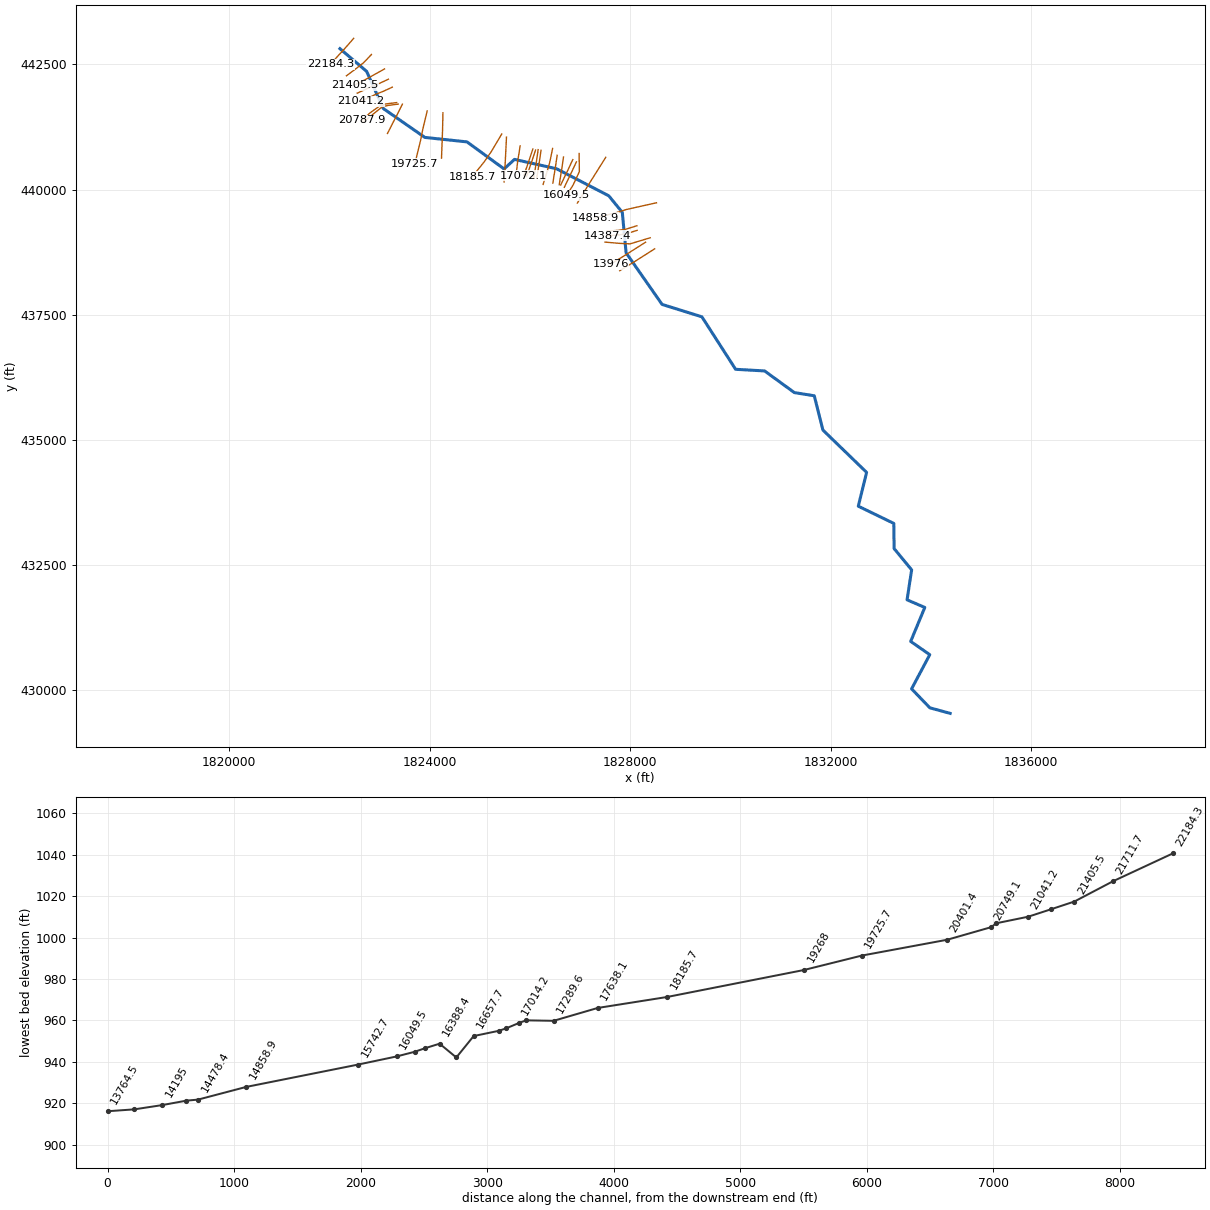
--- RobnsnRn.prj (project) ---

Proj Title=RobnsnRn
Current Plan=p01
Default Exp/Contr=0,0
English Units
Geom File=g01
Flow File=f01
Plan File=p01
BEGIN DESCRIPTION:
END DESCRIPTION:
DSS Export Rating Curves= 0
DSS Export Rating Curve Sorted= 0
DSS Export Volume Flow Curves= 0
DXF OffsetX= 0
DXF OffsetY= 0
DXF ScaleX= 0
DXF ScaleY= 0

--- RobnsnRn.p01 (plan) ---

Plan Title=Floodplain
Program Version=4.00
Geom File=g01
Flow File=f01
K Sum by GR=0
Std Step Tol=0.01
Critical Tol=0.01
Num of Std Step Trials=20
Max Error Tol=0.3
Flow Tol Ratio=0.001
Split Flow NTrial=30
Split Flow Tol=0.02
Split Flow Ratio=0.02
Log Output Level=0
Friction Slope Method=1
Unsteady Friction Slope Method=2
Unsteady Bridges Friction Slope Method=1
Global Log Level=0
CheckData=False
Run HTab=0
Run UNet=0
Run PostProcess=0
UNET Theta=0
UNET Theta Warmup=0
UNET ZTol=0
UNET ZSATol=0
UNET MxIter=0
UNET MaxInSteps=0
UNET DtIC=0
UNET DtMin=0
UNET MaxCRTS=0
UNET WFStab=0
UNET SFStab=0
UNET WFX=0
UNET SFX=0
UNET DSS MLevel=0
UNET DZMax Abort=0
UNET Convert EG Bridges=0
UNET Use Existing IB Tables=0
UNET Froude Limit=0
UNET Froude Power=0
Write IC File=0
Echo Input=False
Echo Output=False
Write Detailed=0

--- RobnsnRn.f01 (steady flow) ---

Flow Title=NFF Regression Equation
Program Version=4.10
Number of Profiles= 1
Profile Names=P100yr
River Rch & RM=RobnsnRn,Main            ,22184.3
     473
River Rch & RM=RobnsnRn,Main            ,20787.9
     502
River Rch & RM=RobnsnRn,Main            ,20401.4
     645
River Rch & RM=RobnsnRn,Main            ,18185.7
     771
River Rch & RM=RobnsnRn,Main            ,16049.5
     822
River Rch & RM=RobnsnRn,Main            ,15742.7
    1029
River Rch & RM=RobnsnRn,Main            ,14858.9
    1143
River Rch & RM=RobnsnRn,Main            ,13764.5
    1244
River Rch & RM=RobnsnRn,Main            ,12178.2
    1376
River Rch & RM=RobnsnRn,Main            ,8955
    1492
River Rch & RM=RobnsnRn,Main            ,6299.6
    1553
River Rch & RM=RobnsnRn,Main            ,5809.4
    1785
River Rch & RM=RobnsnRn,Main            ,5241.8
    1791
River Rch & RM=RobnsnRn,Main            ,5017.3
    2143
River Rch & RM=RobnsnRn,Main            ,395.1
    2194
Boundary for River Rch & Prof#=RobnsnRn,Main            , 1
Up Type= 0
Dn Type= 3
Dn Slope=0.00505
DSS Import GetInterval= 0
DSS Import GetPeak= 0
DSS Import FillOption= 0

--- RobnsnRn.g01 (geometry) ---

Geom Title=USGS 10m DEM
Program Version=4.10

River Reach=RobnsnRn        ,Main
Reach XY= 30
     1822209.683      442812.683     1822741.893      442359.199
     1823074.081      441617.316     1823903.204      441040.551
     1824743.991      440951.196     1825484.023       440411.08
     1825691.141      440602.053     1826532.269      440413.923
     1827571.926      439874.856     1827842.213      439543.304
     1827917.573      438735.726     1828635.536      437706.151
      1829429.66      437458.368     1830101.974      436410.535
     1830680.749        436377.7      1831274.18      435945.401
     1831671.161      435881.973     1831843.745      435197.086
     1832715.231      434352.348     1832549.455      433677.231
     1833258.048      433333.025     1833263.654      432831.212
     1833613.465       432405.96     1833522.168      431807.724
     1833876.305      431655.563     1833594.485      430977.402
     1833975.049         430712.     1833612.744      430029.515
     1833977.051      429651.353     1834381.534      429540.249

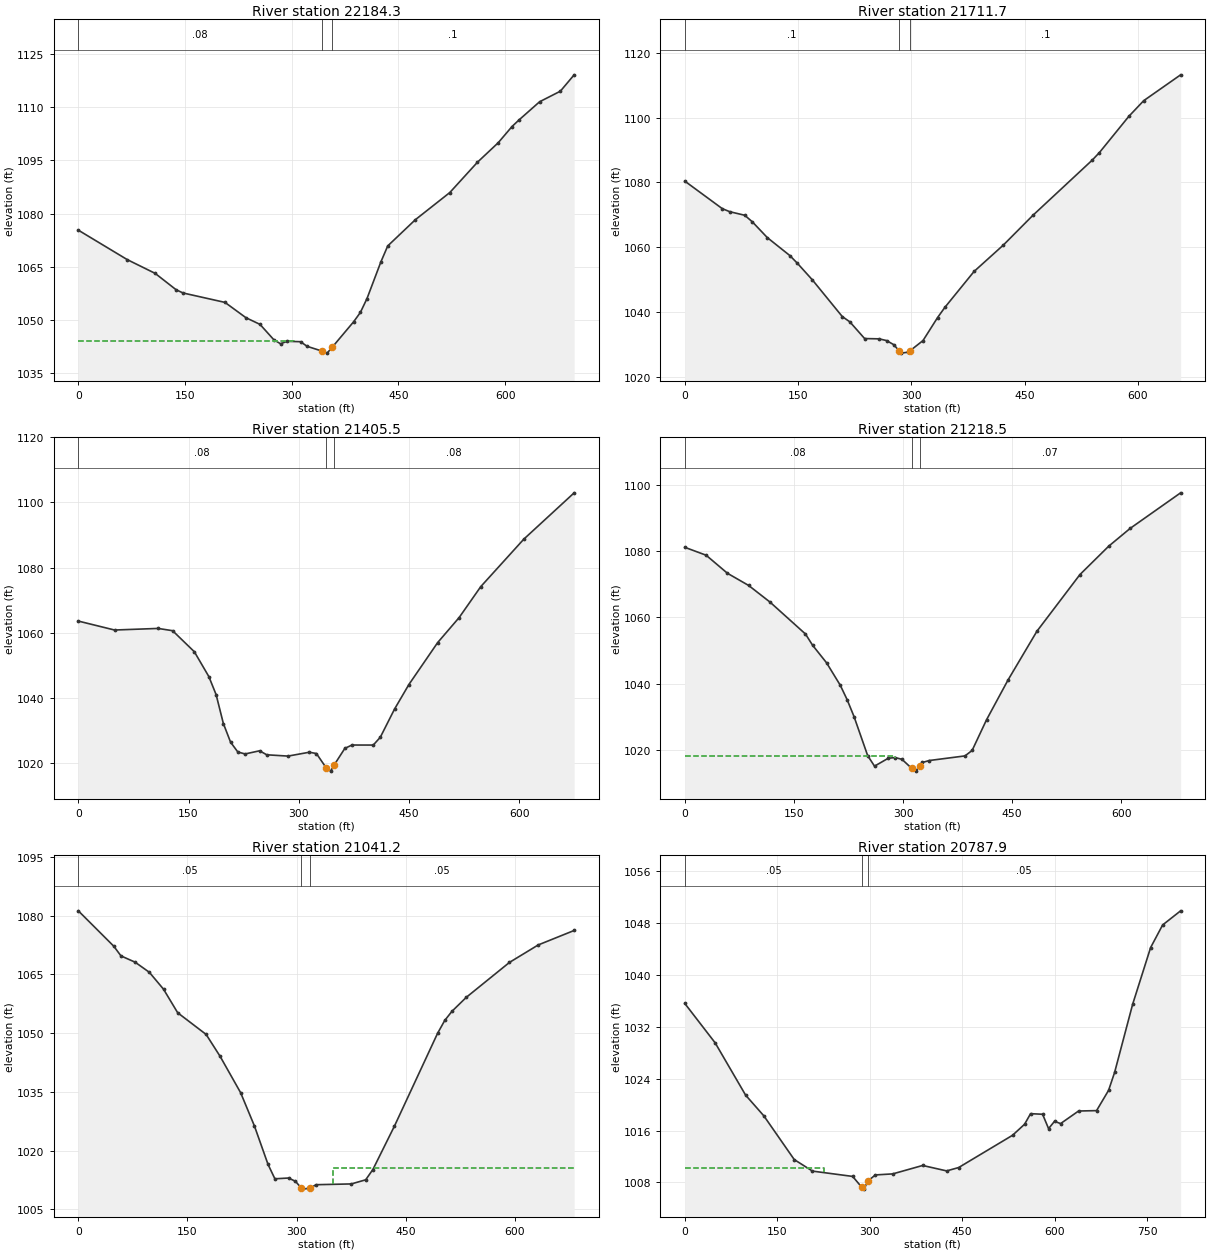
Type RM Length L Ch R = 1 ,22184.3 ,476.2,472.6,469
XS GIS Cut Line= 4
     1822483.663      443018.962     1822302.673       442811.93
     1822214.131      442715.576     1822017.517      442500.732
#Sta/Elev= 30
       0 1075.35    68.8 1067.05     108 1063.18   137.5 1058.56   147.3 1057.65
   206.2    1055   235.7 1050.68   255.4 1048.81     275 1044.45   284.3 1043.35
   293.7 1044.04   312.4 1043.93   321.7 1042.62   341.9 1041.33   349.8 1040.71
   356.9 1042.36   387.2 1049.58   396.5 1052.16   405.8 1056.06   425.3 1066.38
     435 1070.91   473.8 1078.29   522.3 1085.95   561.2  1094.5   590.3 1099.97
   609.7 1104.54   619.4 1106.37   648.5 1111.52   677.7  1114.5   697.1 1119.11
#Mann= 3 , 0 , 0
       0     .08       0   341.9    .045       0   356.9      .1       0
#XS Ineff= 2 , 0
          303.21 1044.17
Permanent Ineff=
       F       F
Bank Sta=341.9,356.9
XS Rating Curve= 0 ,0
Exp/Cntr=0.3,0.1

Type RM Length L Ch R = 1 ,21711.7 ,309.6,306.2,302.6
XS GIS Cut Line= 4
     1822837.829      442696.045     1822680.277       442530.68
     1822535.746      442417.399      1822339.63      442271.491
#Sta/Elev= 30
       0 1080.41    49.6 1071.91    59.6 1070.96    79.4 1069.86    89.4 1067.84
   109.2 1062.97     139 1057.43     149 1055.05   168.8 1049.93   208.5 1038.57
   218.5 1036.94   238.1 1031.77   257.4 1031.68   267.1 1031.15   276.7 1029.88
   283.5 1028.05   286.4 1027.27   296.1 1027.58   298.5 1028.05   315.4 1031.15
   334.7 1038.26   344.4 1041.42     383  1052.5   421.8 1060.66   460.9 1069.84
   539.2 1086.84   548.9 1089.21     588 1100.44   607.6 1105.26   656.5 1113.25
#Mann= 3 , 0 , 0
       0      .1       0   283.5    .045       0   298.5      .1       0
Bank Sta=283.5,298.5
XS Rating Curve= 0 ,0
Exp/Cntr=0.3,0.1

Type RM Length L Ch R = 1 ,21405.5 ,189.8,187,184.1
XS GIS Cut Line= 4
     1823098.745      442407.776      1822883.09      442287.957
     1822722.654      442198.615     1822506.173      442085.095
#Sta/Elev= 30
       0 1063.56    49.3 1060.81   108.6  1061.3   128.3  1060.6   157.9 1054.13
   177.6 1046.52   187.5 1040.97   197.4 1032.07   207.2 1026.35   217.1 1023.32
     227 1022.73   246.7  1023.7   256.4 1022.47   285.4 1022.07   314.4 1023.26
     324 1022.86  337.14 1018.53   343.4 1017.45   348.2 1019.35   362.7 1024.44
   372.4 1025.47   401.4 1025.46     411 1027.87   430.3  1036.5   449.9 1044.07
     489 1056.94   518.3 1064.65   547.7 1074.15   606.3 1088.74   674.8 1102.97
#Mann= 3 , 0 , 0
       0     .08       0  337.14    .045       0   348.2     .08       0
Bank Sta=337.14,348.2
XS Rating Curve= 0 ,0
Exp/Cntr=0.3,0.1

Type RM Length L Ch R = 1 ,21218.5 ,177.3,177.4,177.3
XS GIS Cut Line= 4
     1823175.843      442202.649     1823007.657      442124.524
     1822859.002      442064.845     1822554.098      441923.786
#Sta/Elev= 30
       0 1081.12    29.3 1078.74    58.6  1073.3    87.8 1069.62   117.1 1064.62
   165.9 1054.99   175.7  1051.6   194.9 1046.31   213.7 1039.56   223.1 1035.23
   232.6 1030.13   251.4 1018.34   260.8 1015.17   279.7 1017.55   289.1 1017.76
   298.5 1017.23   311.7 1014.56   317.4 1013.67  322.91 1015.16   326.7 1016.28
   336.2 1016.87   385.2 1018.26     395 1019.91   414.8 1029.15   444.4 1041.16
     484 1055.81   543.2 1072.91   582.8 1081.47   612.4 1086.85   681.6 1097.54
#Mann= 3 , 0 , 0
       0     .08       0   311.7    .045       0  322.91     .07       0
#XS Ineff= 2 , 0
          289.34 1018.32
Permanent Ineff=
       F       F
Bank Sta=311.7,322.91
XS Rating Curve= 0 ,0
Exp/Cntr=0.3,0.1

Type RM Length L Ch R = 1 ,21041.2 ,255.2,253.3,250.5
XS GIS Cut Line= 4
       1823253.1      442043.794     1823084.914      441965.669
     1822936.259      441905.991     1822631.355      441764.932
#Sta/Elev= 30
       0 1081.27    48.8 1072.21    58.6 1069.75    78.1 1068.14    97.6 1065.56
   117.1 1061.24   136.6 1055.21   175.7 1049.67   194.9 1044.07   223.1 1034.78
     242 1026.31   260.8 1016.44   270.2 1012.77   289.1 1012.97   298.5 1012.12
  306.37 1010.45   307.9 1010.13  318.16 1010.36   326.8 1011.26   375.3 1011.46
     395 1012.51   404.9 1015.14   434.6 1026.26   493.8 1049.94   503.7 1053.25
   513.6 1055.58   533.4 1059.17   592.7 1068.09   632.2 1072.55   681.6 1076.25
#Mann= 3 , 0 , 0
       0     .05       0  306.37    .045       0  318.16     .05       0
#XS Ineff= 2 , 0
                          350.15         1015.43
Permanent Ineff=
       F       F
Bank Sta=306.37,318.16
XS Rating Curve= 0 ,0
Exp/Cntr=0.3,0.1

Type RM Length L Ch R = 1 ,20787.9 ,39,38.8,43.2
XS GIS Cut Line= 5
     1823340.954      441736.409      1823125.59      441709.066
     1823018.819       441680.42      1822813.09      441533.284
     1822646.488       441383.47
#Sta/Elev= 30
       0  1035.6    49.3 1029.52    98.7 1021.46   128.3 1018.26   177.6 1011.52
   207.2 1009.74   272.4 1008.92   287.3 1007.23   290.8 1006.96  296.99  1008.2
   309.2 1009.15   337.4 1009.31     386 1010.61   424.9 1009.77   444.4 1010.29
   531.9 1015.27   551.4 1016.97   561.1  1018.6   580.6 1018.51   590.3  1016.3
     600 1017.42   609.8 1017.07     639 1019.01   668.2 1019.07   687.7  1022.2
   697.5 1024.97   726.7 1035.46   755.9 1044.22   775.4 1047.71   804.6 1049.89
#Mann= 3 , 0 , 0
       0     .05       0   287.3    .045       0  296.99     .05       0
#XS Ineff= 2 , 0
          226.65 1010.18  377.12         1010.36
Permanent Ineff=
       F       F
Bank Sta=287.3,296.99
XS Rating Curve= 0 ,0
Exp/Cntr=0.3,0.1

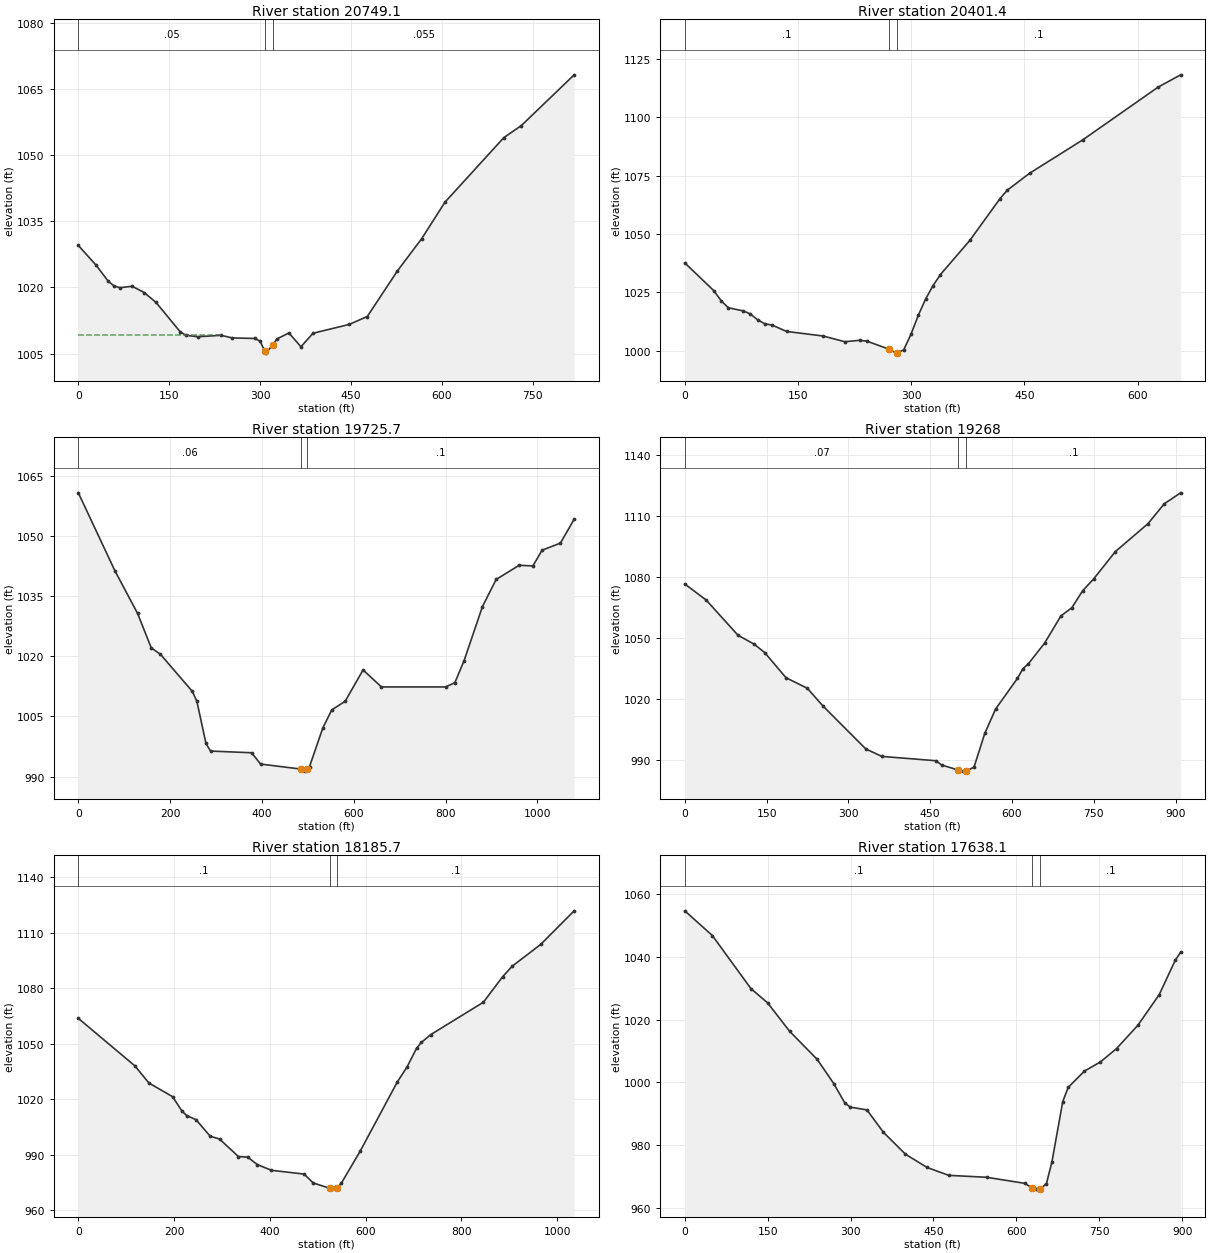
Type RM Length L Ch R = 1 ,20749.1 ,327,347.7,362.7
XS GIS Cut Line= 5
     1823372.204      441705.159      1823156.84      441677.816
     1823050.069       441649.17     1822864.131        441499.3
     1822668.623      441340.502
#Sta/Elev= 30
       0 1029.56    29.6 1025.02    49.3 1021.43    59.2 1020.32    69.1 1019.96
    88.8 1020.28   108.6 1018.86   128.3  1016.6   167.8 1009.99   177.6 1009.13
   197.4 1008.81   235.5 1009.14   253.9 1008.55   290.8 1008.42     300 1007.84
  307.52 1005.57   309.2 1005.09   321.3 1006.99   327.6  1008.3   347.5 1009.68
   367.4 1006.54   387.3  1009.6     447 1011.61   476.9 1013.41   526.6 1023.77
   566.5 1031.06   605.2  1039.4   702.1 1054.03   731.1 1056.78   818.3 1068.31
#Mann= 3 , 0 , 0
       0     .05       0  307.52    .045       0   321.3    .055       0
#XS Ineff= 2 , 0
          237.21  1009.3  347.61         1009.64
Permanent Ineff=
       F       F
Bank Sta=307.52,321.3
XS Rating Curve= 0 ,0
Exp/Cntr=0.3,0.1

Type RM Length L Ch R = 1 ,20401.4 ,668.8,675.7,682.6
XS GIS Cut Line= 4
     1823454.984      441705.503     1823361.234      441515.399
     1823275.297      441351.336     1823158.109      441119.566
#Sta/Elev= 30
       0 1037.63    38.5 1025.71    48.2 1021.43    57.8 1018.39    77.1 1017.12
    86.7 1015.81    96.4 1013.31     106 1011.56   115.6 1011.02   134.9 1008.28
   183.1 1006.34     212 1003.89   231.5 1004.49   241.2 1004.14   270.4 1000.71
   280.2  999.01   281.5  999.19     290 1000.39   299.7 1007.11   309.4 1015.23
   319.2 1022.27   328.9  1027.9   338.7 1032.64   377.7 1047.27   417.2 1064.94
   427.1 1068.69   457.1 1076.03     527  1090.2   626.9 1112.78   656.9 1118.08
#Mann= 3 , 0 , 0
       0      .1       0   270.4    .045       0   281.5      .1       0
Bank Sta=270.4,281.5
XS Rating Curve= 0 ,0
Exp/Cntr=0.3,0.1

Type RM Length L Ch R = 1 ,19725.7 ,455.5,457.7,459
XS GIS Cut Line= 4
     1823950.096      441571.075     1823859.819      441194.338
     1823816.416      440975.588     1823705.305      440518.991
#Sta/Elev= 30
       0  1060.7    79.5 1041.32   129.1 1030.64   158.9 1022.06   178.8 1020.48
   248.3 1011.23   258.3 1008.75   278.1  998.24   288.1  996.35   377.5  995.93
   397.1  993.11   484.4  991.87   494.1  991.35   498.5  991.87   503.8   992.5
   532.8 1002.14   552.2 1006.61   581.3 1008.75   620.4 1016.57   660.4 1012.33
   800.4 1012.33   820.4  1013.4   840.4 1018.86   880.4 1032.33   910.4 1039.12
   960.4 1042.64   990.4 1042.49  1010.4  1046.4  1050.3 1048.17  1080.3 1054.12
#Mann= 3 , 0 , 0
       0     .06       0   484.4    .045       0   498.5      .1       0
Bank Sta=484.4,498.5
XS Rating Curve= 0 ,0
Exp/Cntr=0.3,0.1

Type RM Length L Ch R = 1 ,19268   ,1092.2,1082.3,1071.6
XS GIS Cut Line= 4
     1824264.012      441534.062     1824256.199        441182.5
     1824248.387      440974.166     1824235.366      440625.208
#Sta/Elev= 30
       0 1076.64    39.1 1068.75    97.7 1051.33     127    1047   146.5 1042.84
   185.6 1030.42   224.7 1025.24     254 1016.32   332.1  995.28   361.6  991.63
   460.8   989.5   470.8  987.41   501.5  984.92   510.5  984.38   516.5   984.5
   530.4  986.34   550.2 1003.03   570.1 1015.05     610 1030.08     620 1034.85
     630 1037.29   659.9  1047.5   689.8 1060.91   709.8 1064.93   729.7 1073.34
   749.7 1079.11   789.6 1092.61   849.5 1106.39   879.4 1116.22   909.3 1121.58
#Mann= 3 , 0 , 0
       0     .07       0   501.5    .045       0   516.5      .1       0
Bank Sta=501.5,516.5
XS Rating Curve= 0 ,0
Exp/Cntr=0.3,0.1

Type RM Length L Ch R = 1 ,18185.7 ,530.2,547.6,556.6
XS GIS Cut Line= 4
     1825436.207      441108.227     1825231.346      440761.005
     1825087.249      440552.672     1824849.949      440257.152
#Sta/Elev= 30
       0 1063.76     118 1038.06   147.5 1028.75   196.7 1021.39   216.3 1013.66
   226.2 1011.15   245.8 1008.92   275.3    1000     295  998.43   334.3  988.98
     354  988.62   373.6  984.65   403.2  981.54   471.4  979.48   490.8  974.66
   525.1   971.8   529.8  971.34   539.6  971.77   549.3  974.57   588.3  991.73
   666.4 1029.45   686.4  1037.4   706.3 1047.52   716.3  1050.7   736.2 1054.99
     846 1072.49   885.9 1086.22   905.8 1091.91   965.6 1103.76  1035.5 1121.94
#Mann= 3 , 0 , 0
       0      .1       0   525.1    .045       0   539.6      .1       0
Bank Sta=525.1,539.6
XS Rating Curve= 0 ,0
Exp/Cntr=0.3,0.1

Type RM Length L Ch R = 1 ,17638.1 ,347.1,348.6,345.1
XS GIS Cut Line= 4
     1825531.694      441047.463     1825512.596      440658.575
     1825495.235      440325.241     1825483.082       440151.63
#Sta/Elev= 30
       0 1054.58    49.9 1046.72   119.8  1029.8   149.8 1025.32   189.7 1016.26
   239.6 1007.32   269.6  999.61   289.5  993.48   299.5  992.13   329.5  991.26
   359.4  984.13   399.2  977.18   438.4  972.94   477.7  970.43   546.4  969.82
   615.2  967.89   628.5  966.44   634.8  966.05   643.5  966.15   654.4  967.81
   664.2  974.61   683.9  993.88   693.7   998.4   723.1  1003.6   752.2 1006.52
   781.2 1010.76   819.8 1018.17   858.5 1027.93   887.5 1038.87   897.2 1041.42
#Mann= 3 , 0 , 0
       0      .1       0   628.5    .045       0   643.5      .1       0
Bank Sta=628.5,643.5
XS Rating Curve= 0 ,0
Exp/Cntr=0.3,0.1

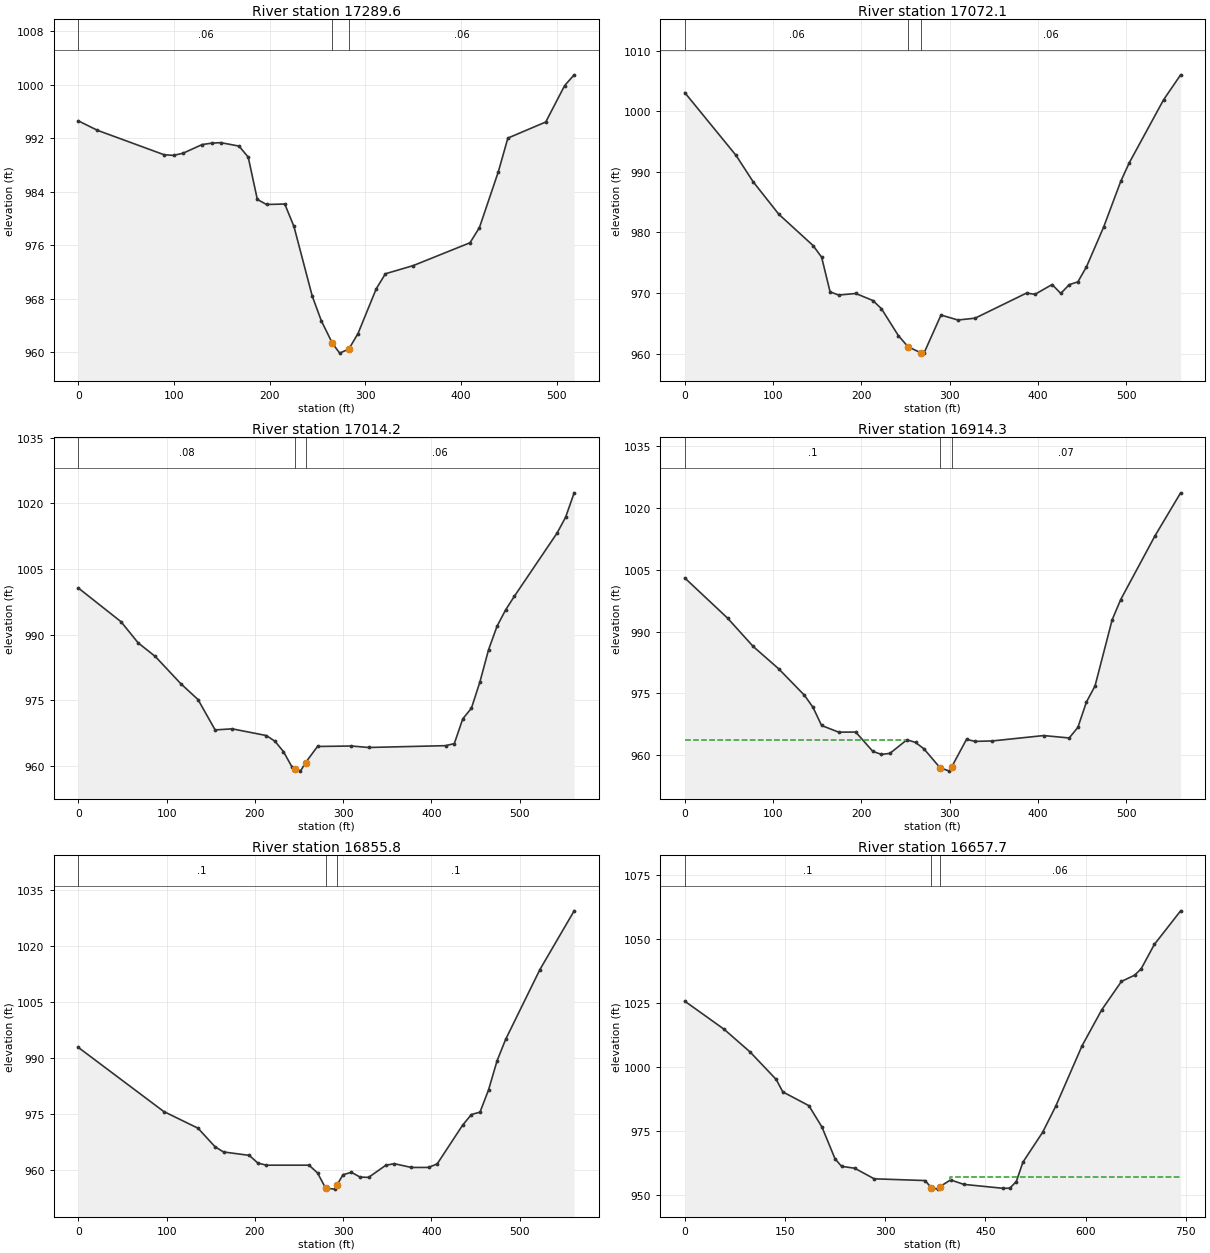
Type RM Length L Ch R = 1 ,17289.6 ,221.6,217.4,213.3
XS GIS Cut Line= 4
     1825804.046      440870.684     1825782.188      440733.094
     1825751.549      440534.641     1825731.129      440357.663
#Sta/Elev= 30
       0  994.61    19.9   993.2    89.6  989.54    99.5  989.44   109.5  989.77
   129.4  991.06   139.3  991.27   148.9  991.35     168  990.83   177.6  989.18
   187.1  982.85   196.7  982.09   215.8  982.16   225.4   978.8   244.5  968.38
   254.1  964.65   265.6  961.31   273.2  959.84   282.8  960.46   292.3  962.76
   311.4  969.47     321  971.72     350  972.94   409.4  976.36   419.3  978.64
   439.1  987.02     449  992.03   488.6  994.44   508.4   999.9   518.3  1001.5
#Mann= 3 , 0 , 0
       0     .06       0   265.6    .045       0   282.8     .06       0
Bank Sta=265.6,282.8
XS Rating Curve= 0 ,0
Exp/Cntr=0.3,0.1

Type RM Length L Ch R = 1 ,17072.1 ,57.9,57.9,57.9
XS GIS Cut Line= 4
     1826058.213      440810.658     1825985.213      440589.974
     1825959.602      440517.255     1825877.657      440278.713
#Sta/Elev= 30
       0 1003.09    58.1  992.72    77.5  988.36   106.5  983.01   145.3  977.84
     155  975.93   164.6   970.2   174.3  969.66   193.7  969.92   213.1  968.76
   222.8  967.41   242.1  962.94   252.8  961.15   267.8  960.09     271  960.07
   290.3  966.36   309.5  965.54   328.9  965.84   387.2  969.99   396.8  969.78
   416.2   971.4     426  969.93   435.6  971.38   445.4  971.84   455.1  974.32
   474.5  980.86   493.9  988.42   503.6   991.5   542.4 1001.89   561.8 1006.03
#Mann= 3 , 0 , 0
       0     .06       0   252.8    .045       0   267.8     .06       0
Bank Sta=252.8,267.8
XS Rating Curve= 0 ,0
Exp/Cntr=0.3,0.1

Type RM Length L Ch R = 1 ,17014.2 ,95.9,99.9,103.9
XS GIS Cut Line= 4
     1826111.685      440788.436     1826038.685      440567.752
     1826013.074      440495.033     1825931.129      440256.491
#Sta/Elev= 30
       0 1000.66    48.4  992.94    67.8   988.1    87.2  984.99   116.2  978.74
   135.6  975.13     155  968.18   174.3  968.43   213.1  966.89   222.8  965.59
   232.4  963.23   242.1   959.7     246  959.31   251.7  958.75   257.4  960.69
     271  964.39   309.5   964.5   328.9  964.16   416.2  964.58     426  965.05
   435.6  970.72   445.4  973.15   455.1  979.23   464.8  986.52   474.5  991.95
   484.2  995.67   493.9  998.72   542.4 1013.22   552.1 1016.85   561.8 1022.44
#Mann= 3 , 0 , 0
       0     .08       0     246    .045       0   257.4     .06       0
Bank Sta=246,257.4
XS Rating Curve= 0 ,0
Exp/Cntr=0.3,0.1

Type RM Length L Ch R = 1 ,16914.3 ,58.5,58.5,58.4
XS GIS Cut Line= 4
     1826163.821      440796.658     1826130.391       440566.63
     1826117.843      440490.561     1826078.717       440241.39
#Sta/Elev= 30
       0 1002.97    48.4  993.26    77.5  986.38   106.5  980.95   135.6  974.56
   145.3  971.63     155  967.25   174.3  965.64   193.7  965.66   213.1  960.97
   222.8  960.25   232.4   960.5   251.7  963.79   261.4  963.15     271  961.59
   289.3     957   299.9   956.2  302.52  957.27   319.2   963.9   328.9   963.4
   348.4  963.51   406.6  964.81   435.6  964.23   445.4  966.81   455.1  972.95
   464.8  976.81   484.2  992.83   493.9  997.74   532.7 1013.15   561.8 1023.58
#Mann= 3 , 0 , 0
       0      .1       0   289.3    .045       0  302.52     .07       0
#XS Ineff= 2 , 0
          251.13  963.75
Permanent Ineff=
       F       F
Bank Sta=289.3,302.52
XS Rating Curve= 0 ,0
Exp/Cntr=0.3,0.1

Type RM Length L Ch R = 1 ,16855.8 ,200.2,198.1,195.2
XS GIS Cut Line= 4
     1826220.347      440784.093     1826186.918      440554.065
     1826174.369      440477.996     1826135.243      440228.825
#Sta/Elev= 30
       0  992.87    96.8  975.74   135.6  971.28     155   966.3   164.6  964.93
   193.7  964.02   203.4  961.97   213.1   961.4   261.4   961.4     271  959.34
   280.2  955.28   290.3     955   292.8  955.99   299.9  958.86   309.5  959.49
   319.2  958.22   328.9  958.14   348.4  961.38     358   961.8   377.4  960.79
   396.8   960.8   406.6  961.74   435.6  972.16   445.4  974.94   455.1  975.57
   464.8  981.52   474.5  989.33   484.2  995.04     523 1013.68   561.8 1029.37
#Mann= 3 , 0 , 0
       0      .1       0   280.2    .045       0   292.8      .1       0
Bank Sta=280.2,292.8
XS Rating Curve= 0 ,0
Exp/Cntr=0.3,0.1

Type RM Length L Ch R = 1 ,16657.7 ,134.8,137.1,139.9
XS GIS Cut Line= 4
     1826451.338      440819.132     1826394.047      440541.354
     1826366.269      440440.659     1826262.102      440102.118
#Sta/Elev= 30
       0 1025.89    58.7 1014.95    97.8 1006.04   136.9   995.3   146.7  990.47
   185.8  985.07   205.4   976.7   224.9  964.34   234.7  961.38   254.3  960.65
   283.6  956.51   359.6  955.83   369.2  953.04   378.6  952.48  381.53  953.38
   397.9  956.09   417.6  954.34   476.6   952.8   486.5  952.85   496.3  955.44
   506.2  963.01   535.7  974.68   555.3  984.85   594.7 1008.45   624.2 1022.52
   653.7 1033.61   673.4 1036.03   683.2 1038.53   702.9 1048.03   742.3 1061.18
#Mann= 3 , 0 , 0
       0      .1       0   369.2    .045       0  381.53     .06       0
#XS Ineff= 2 , 0
                           396.6          957.36
Permanent Ineff=
       F       F
Bank Sta=369.2,381.53
XS Rating Curve= 0 ,0
Exp/Cntr=0.3,0.1

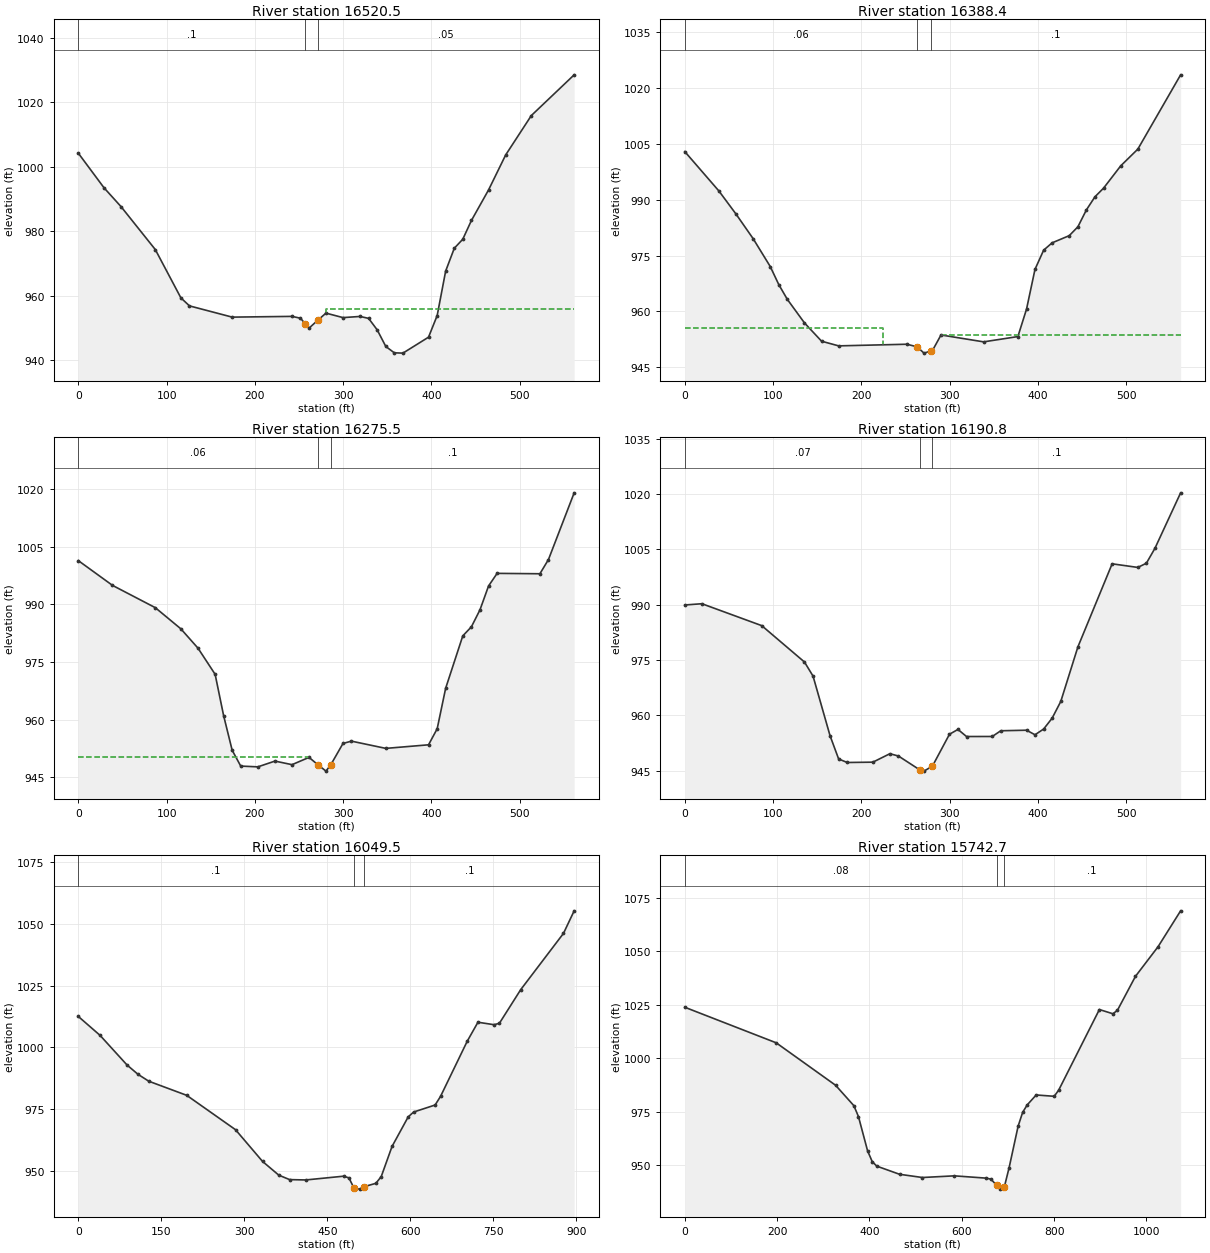
Type RM Length L Ch R = 1 ,16520.5 ,132.3,132.1,132.3
XS GIS Cut Line= 4
     1826541.729      440683.246     1826508.299      440453.218
     1826495.751      440377.149     1826456.625      440127.978
#Sta/Elev= 30
       0 1004.16    29.1  993.43    48.4  987.58    87.2  974.27   116.2  959.28
   125.9  956.79   174.3   953.3   242.1  953.53   251.7  952.96   256.9  951.31
   261.4  949.88     271  952.26   280.6  954.54   299.9  953.15   319.2  953.51
   328.9  952.91   338.6  949.36   348.4  944.19     358  942.23   367.8  942.13
   396.8  947.08   406.6   953.8   416.2  967.59     426  974.68   435.6  977.47
   445.4  983.29   464.8  992.76   484.2 1003.62   513.3 1015.85   561.8 1028.48
#Mann= 3 , 0 , 0
       0      .1       0   256.9    .045       0     271     .05       0
#XS Ineff= 2 , 0
                          280.94           955.9
Permanent Ineff=
       F       F
Bank Sta=256.9,271
XS Rating Curve= 0 ,0
Exp/Cntr=0.3,0.1

Type RM Length L Ch R = 1 ,16388.4 ,119.1,112.9,105.9
XS GIS Cut Line= 4
     1826669.089       440650.89     1826635.659      440420.862
      1826623.11      440344.793     1826583.985      440095.622
#Sta/Elev= 30
       0 1002.95    38.7  992.35    58.1  986.14    77.5  979.53    96.8  972.07
   106.5   967.2   116.2  963.23   135.6  956.91     155  951.99   174.3  950.74
   251.7  951.18   263.4  950.47     271  948.79   278.4  949.32   280.6  949.48
   290.3  953.67   338.6  951.82   377.4  953.24   387.2  960.61   396.8  971.31
   406.6  976.46   416.2  978.43   435.6  980.36   445.4  982.74   455.1  987.31
   464.8  990.82   474.5  993.13   493.9  999.11   513.3 1003.61   561.8 1023.58
#Mann= 3 , 0 , 0
       0     .06       0   263.4    .045       0   278.4      .1       0
#XS Ineff= 2 , 0
          224.75  955.49  290.37          953.67
Permanent Ineff=
       F       F
Bank Sta=263.4,278.4
XS Rating Curve= 0 ,0
Exp/Cntr=0.3,0.1

Type RM Length L Ch R = 1 ,16275.5 ,84.7,84.7,84.7
XS GIS Cut Line= 4
     1826853.823      440597.218      1826755.83      440386.439
     1826721.994      440317.163     1826613.054      440089.679
#Sta/Elev= 30
       0 1001.35    38.7  994.92    87.2  989.13   116.2  983.62   135.6   978.6
     155  971.81   164.6  961.09   174.3  952.08     184  947.96   203.4  947.76
   222.8  949.26   242.1  948.33   261.4  950.22   271.2  948.35   280.6  946.65
   286.2  948.36   299.9  953.85   309.5  954.44   348.4  952.56   396.8  953.49
   406.6  957.66   416.2  968.19   435.6  981.79   445.4  984.16   455.1  988.57
   464.8  994.76   474.5  998.04     523  997.94   532.7 1001.64   561.8 1018.97
#Mann= 3 , 0 , 0
       0     .06       0   271.2    .045       0   286.2      .1       0
#XS Ineff= 2 , 0
          261.36  950.34
Permanent Ineff=
       F       F
Bank Sta=271.2,286.2
XS Rating Curve= 0 ,0
Exp/Cntr=0.3,0.1

Type RM Length L Ch R = 1 ,16190.8 ,139.9,141.4,142.1
XS GIS Cut Line= 4
     1826926.027      440552.383     1826828.035      440341.604
     1826794.198      440272.329     1826685.258      440044.845
#Sta/Elev= 30
       0   989.9    19.4  990.24    87.2   984.3   135.6  974.44   145.3  970.63
   164.6  954.45   174.3  948.17     184  947.21   213.1   947.3   232.4  949.59
   242.1  948.96   266.7  945.14     271  944.87   280.6  946.23   299.9  954.87
   309.5  956.17   319.2  954.25   348.4  954.26     358  955.81   387.2  955.96
   396.8  954.73   406.6  956.28   416.2  959.22     426  963.75   445.4  978.54
   484.2 1001.06   513.3 1000.08     523 1001.22   532.7 1005.26   561.8  1020.3
#Mann= 3 , 0 , 0
       0     .07       0   266.7    .045       0   280.6      .1       0
Bank Sta=266.7,280.6
XS Rating Curve= 0 ,0
Exp/Cntr=0.3,0.1

Type RM Length L Ch R = 1 ,16049.5 ,310.4,306.8,303.4
XS GIS Cut Line= 4
     1826980.993      440719.523     1826985.334       440357.11
     1826861.636      440092.353     1826735.768       439886.19
#Sta/Elev= 30
       0 1012.48    39.2 1004.85    88.2  992.81   107.8  989.09   127.3  986.29
   195.9  980.58   284.1  966.68     333  953.84   362.4  948.28   381.9  946.49
   411.1  946.35   479.3  947.87   489.1   947.2  498.43  942.97   508.6  942.64
     517  943.66   537.8  944.99   547.5  947.72     567   959.9   596.2  971.85
     606  973.82   644.9  976.67   654.7  980.16     703  1002.5   722.3 1010.15
   751.3 1009.15     761  1009.7   799.6 1023.33   876.9 1046.09   896.2 1055.21
#Mann= 3 , 0 , 0
       0      .1       0  498.43    .045       0     517      .1       0
Bank Sta=498.43,517
XS Rating Curve= 0 ,0
Exp/Cntr=0.3,0.1

Type RM Length L Ch R = 1 ,15742.7 ,900.1,883.9,866.9
XS GIS Cut Line= 3
     1827511.483      440643.224     1827148.462      440064.649
     1826946.271       439729.94
#Sta/Elev= 30
       0 1023.83     198 1007.18   326.7   987.3   366.3  977.73   376.2  972.64
     396  956.58   405.9  951.61   415.8  949.45   465.2  945.63   514.8  944.12
     584   944.9   653.3  943.82   663.2  943.33   675.5  940.49     683  938.68
   690.5  939.85   692.8  940.21   702.6  948.76   722.1  968.17   731.9  974.63
   741.7   978.1   761.2  982.76   800.3  982.14   810.1  985.09   898.1 1022.76
   927.4 1020.78   937.2  1022.4   976.3 1038.31  1025.2 1052.16  1074.1 1068.97
#Mann= 3 , 0 , 0
       0     .08       0   675.5    .045       0   690.5      .1       0
Bank Sta=675.5,690.5
XS Rating Curve= 0 ,0
Exp/Cntr=0.3,0.1

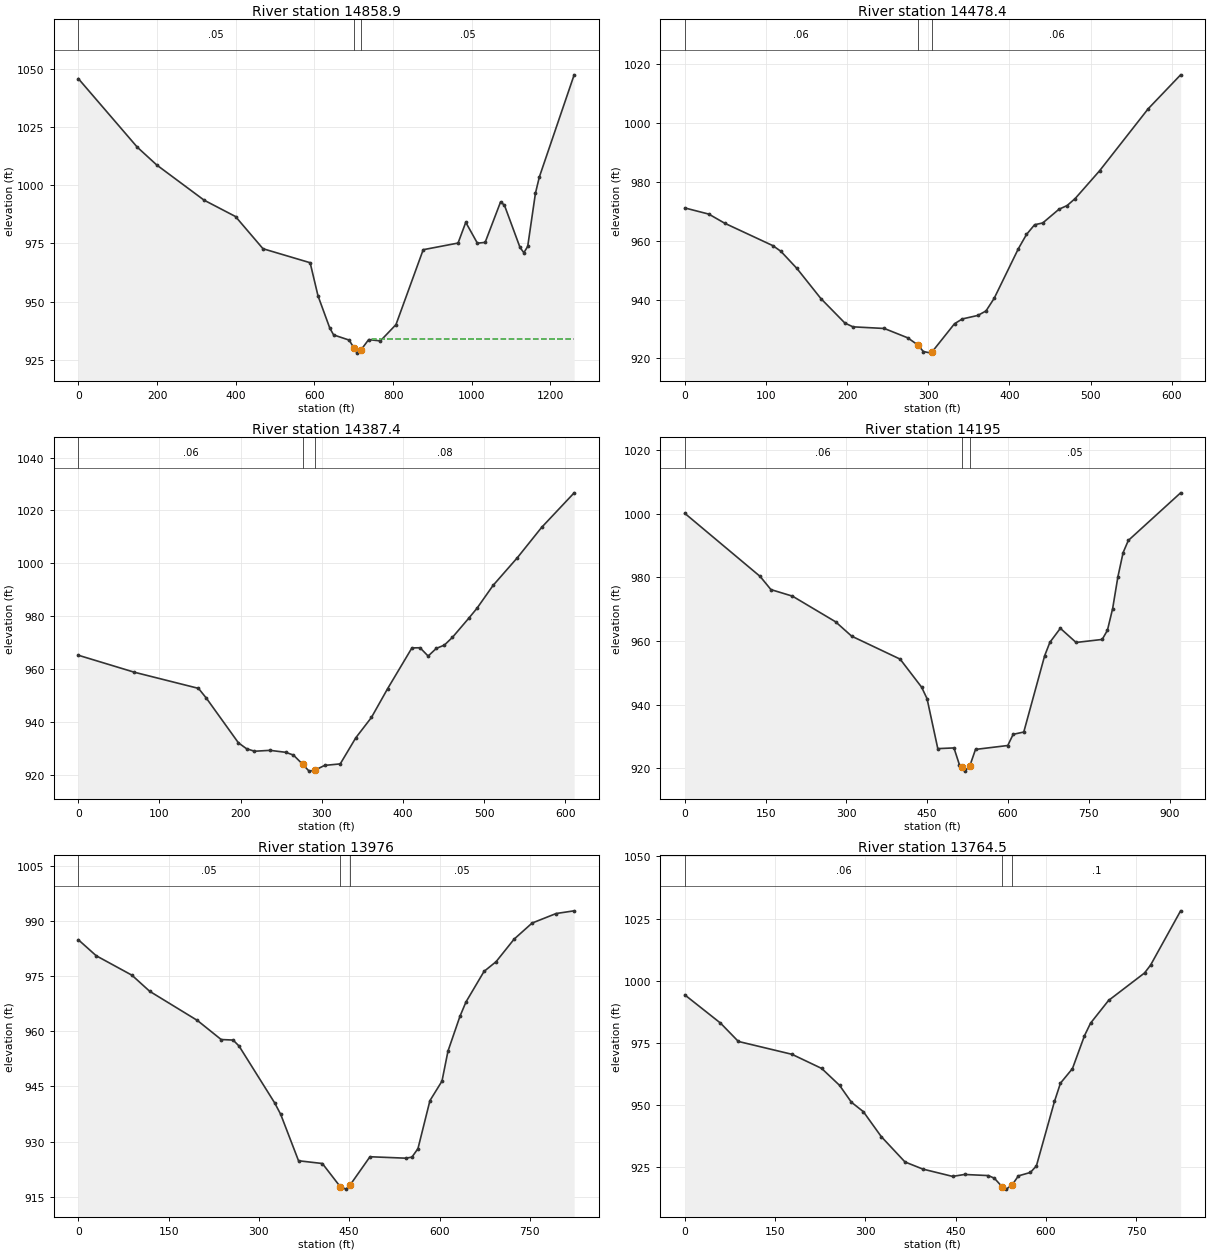
Type RM Length L Ch R = 1 ,14858.9 ,383.5,380.5,377.5
XS GIS Cut Line= 4
     1828523.018      439735.364     1827918.851      439599.948
     1827691.855      439529.201     1827299.483      439435.583
#Sta/Elev= 30
       0  1045.8   149.8 1016.36   199.7 1008.65   319.6   993.6   399.5  986.57
   469.4  972.73   589.2  966.72   609.2   952.5     639  938.72   648.9  935.71
   688.5  933.48  700.41  930.13   708.3  927.89   718.2  929.23     738   933.7
   767.8  933.14   807.4  940.14   876.6  972.31   965.2  975.17   984.8  984.08
  1014.3  975.12    1034  975.45  1073.4   992.9  1083.2  991.37  1122.6  973.32
  1132.4  971.02  1142.2  973.71  1161.9  996.58  1171.8 1003.54  1260.3 1047.43
#Mann= 3 , 0 , 0
       0     .05       0  700.41    .045       0   718.2     .05       0
#XS Ineff= 2 , 0
                          747.44          934.11
Permanent Ineff=
       F       F
Bank Sta=700.41,718.2
XS Rating Curve= 0 ,0
Exp/Cntr=0.3,0.1

Type RM Length L Ch R = 1 ,14478.4 ,91,91,91
XS GIS Cut Line= 4
     1828131.514      439276.294     1827924.483       439211.19
     1827782.556      439186.451     1827533.424      439168.656
#Sta/Elev= 30
       0  971.13    29.6  969.03    49.3  965.91   108.5  958.31   118.4  956.38
   138.1  950.57   167.7  940.31   197.3  931.98   207.2  930.71   245.8  930.15
   274.6  926.98     287  924.58   293.9  922.32   303.5  921.77  304.66  922.19
   332.3  931.76   341.9  933.39   361.1  934.59   371.1  936.11   381.1  940.36
     411  957.28     421  962.11     431  965.42     441  966.02     461  970.68
     471  971.93     481  974.33     511  983.74   570.9 1004.83   610.9 1016.38
#Mann= 3 , 0 , 0
       0     .06       0     287    .045       0  304.66     .06       0
Bank Sta=287,304.66
XS Rating Curve= 0 ,0
Exp/Cntr=0.3,0.1

Type RM Length L Ch R = 1 ,14387.4 ,197.2,192.4,187.5
XS GIS Cut Line= 4
     1828138.285      439185.149     1827931.254      439120.044
     1827789.326      439095.305     1827540.195       439077.51
#Sta/Elev= 30
       0  965.16      69  958.73     148  952.62   157.8  948.89   197.3  931.97
   207.2  929.78     217  928.81   236.2  929.15   255.4  928.41     265  927.37
   276.3   923.9   284.3  921.28   291.3  921.62   303.5  923.45   322.7  924.02
   341.9  933.92   361.1  941.59   381.1  952.52     411  967.93     421     968
     431  964.85     441  967.74     451     969     461  971.96     481  979.16
     491  982.88     511   991.6   540.9 1002.09   570.9  1013.6   610.9 1026.66
#Mann= 3 , 0 , 0
       0     .06       0   276.3    .045       0   291.3     .08       0
Bank Sta=276.3,291.3
XS Rating Curve= 0 ,0
Exp/Cntr=0.3,0.1

Type RM Length L Ch R = 1 ,14195   ,205.2,219.1,232.8
XS GIS Cut Line= 4
     1828399.237      439036.721     1827997.301      438915.707
     1827797.648      438924.388     1827497.865      438950.057
#Sta/Elev= 30
       0 1000.11   139.9  980.28   159.9  976.15   199.9  974.09   279.8  966.05
   309.8  961.52   399.8   954.3   439.7  945.48   449.7   941.9   469.7  926.19
   499.7  926.41   509.7  921.18   514.1  920.27   519.7  919.12   529.1  920.76
   539.7  925.94   599.6  927.17   609.6  930.68   629.3   931.4   668.1  955.38
   677.8  959.59   697.2  963.99   726.4  959.54   774.9  960.49   784.6  963.36
   794.3  970.19     804  980.12   813.7  987.76   823.4  991.59   920.5 1006.55
#Mann= 3 , 0 , 0
       0     .06       0   514.1    .045       0   529.1     .05       0
Bank Sta=514.1,529.1
XS Rating Curve= 0 ,0
Exp/Cntr=0.3,0.1

Type RM Length L Ch R = 1 ,13976   ,211.8,211.5,211
XS GIS Cut Line= 3
     1828306.138      438948.396     1827880.791      438677.563
     1827608.221      438510.896
#Sta/Elev= 30
       0  984.92    29.7  980.57      89  975.28   118.6  970.89   197.8  962.96
   237.3  957.77   257.1  957.63     267     956   326.3   940.5   336.2  937.41
   365.8  924.79   405.4  924.04     435  917.76   444.9  917.07     451  918.08
   484.5  925.88   544.2  925.49   554.2  925.78   564.2  928.08   584.1  941.15
   604.1  946.45   614.1  954.63     634   964.1     644     968     674  976.31
     694  978.95   723.9  985.08   753.8  989.46   793.8  992.06   823.7  992.79
#Mann= 3 , 0 , 0
       0     .05       0     435    .045       0     451     .05       0
Bank Sta=435,451
XS Rating Curve= 0 ,0
Exp/Cntr=0.3,0.1

Type RM Length L Ch R = 1 ,13764.5 ,368.6,370.1,371.5
XS GIS Cut Line= 3
     1828487.779      438816.235     1828062.431      438545.401
     1827789.862      438378.735
#Sta/Elev= 30
       0  994.32    59.3  982.97      89  975.58     178  970.41   227.4  964.72
   257.1  957.92   276.8  951.12   296.6  947.34   326.3  937.32   365.8  927.09
   395.5  924.22   444.9  921.28   464.7  922.06   504.2  921.61   514.2  920.57
   527.2   917.1   534.2  916.16   544.2     918   554.2  921.49   574.1  922.87
   584.1  925.49   614.1  951.43   624.1  958.81     644  964.65     664   977.9
     674  982.92   703.9  992.06   763.8 1003.14   773.8 1006.31   823.7 1028.14
#Mann= 3 , 0 , 0
       0     .06       0   527.2    .045       0   544.2      .1       0
Bank Sta=527.2,544.2
XS Rating Curve= 0 ,0
Exp/Cntr=0.3,0.1