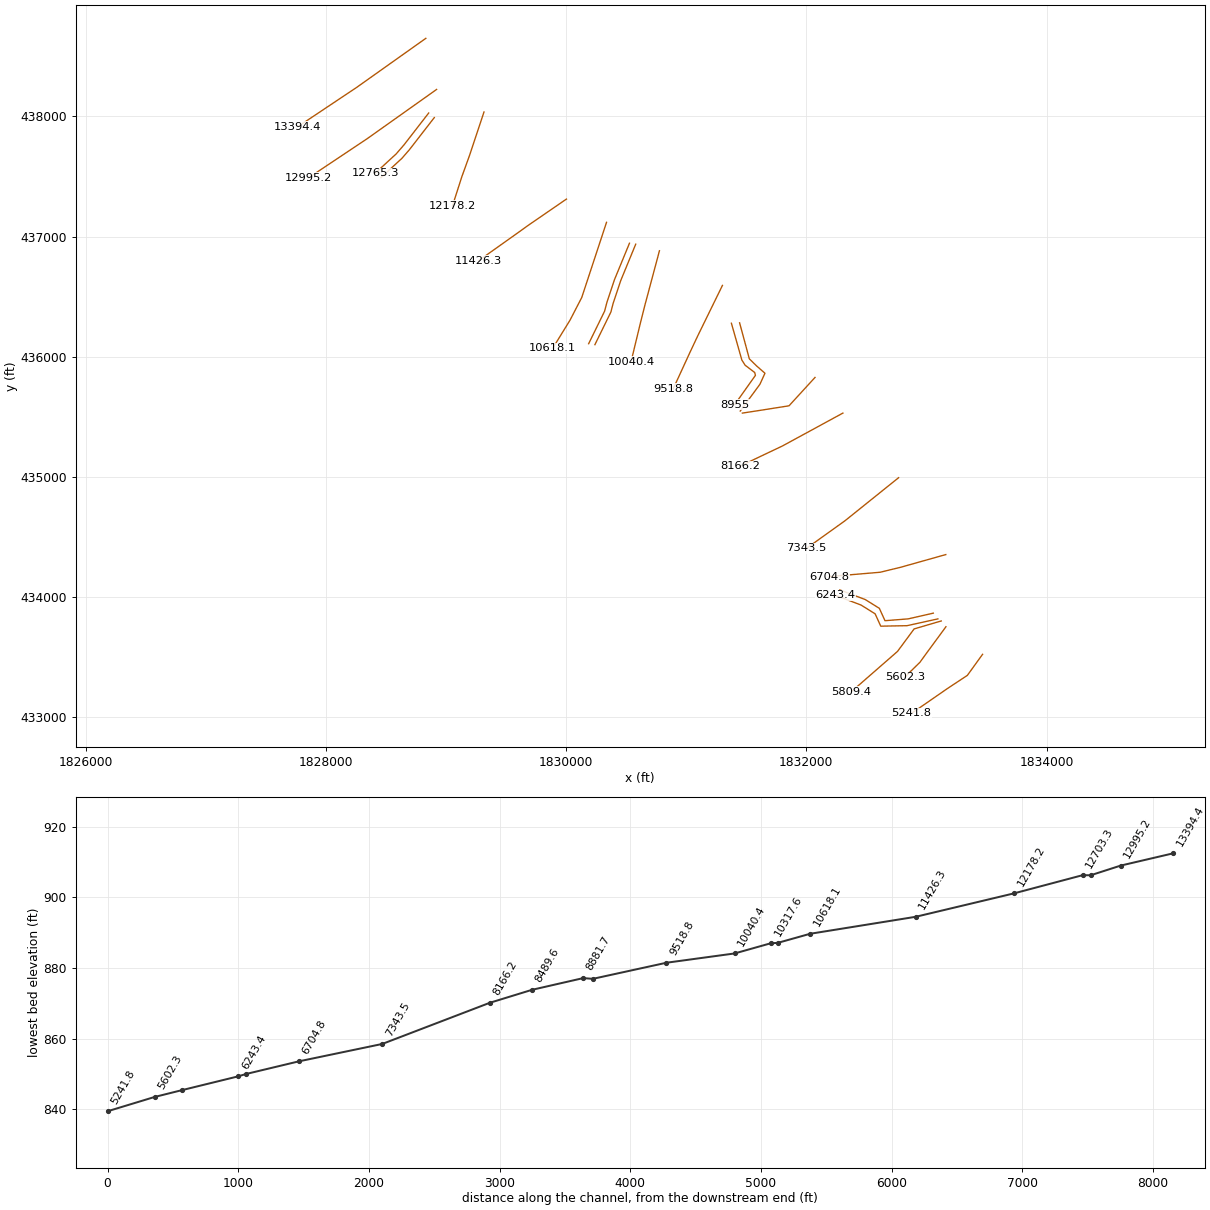
HEC-RAS study RobnsnRn.prj: RobnsnRn

--- RobnsnRn.g01 (geometry) --- (continued)

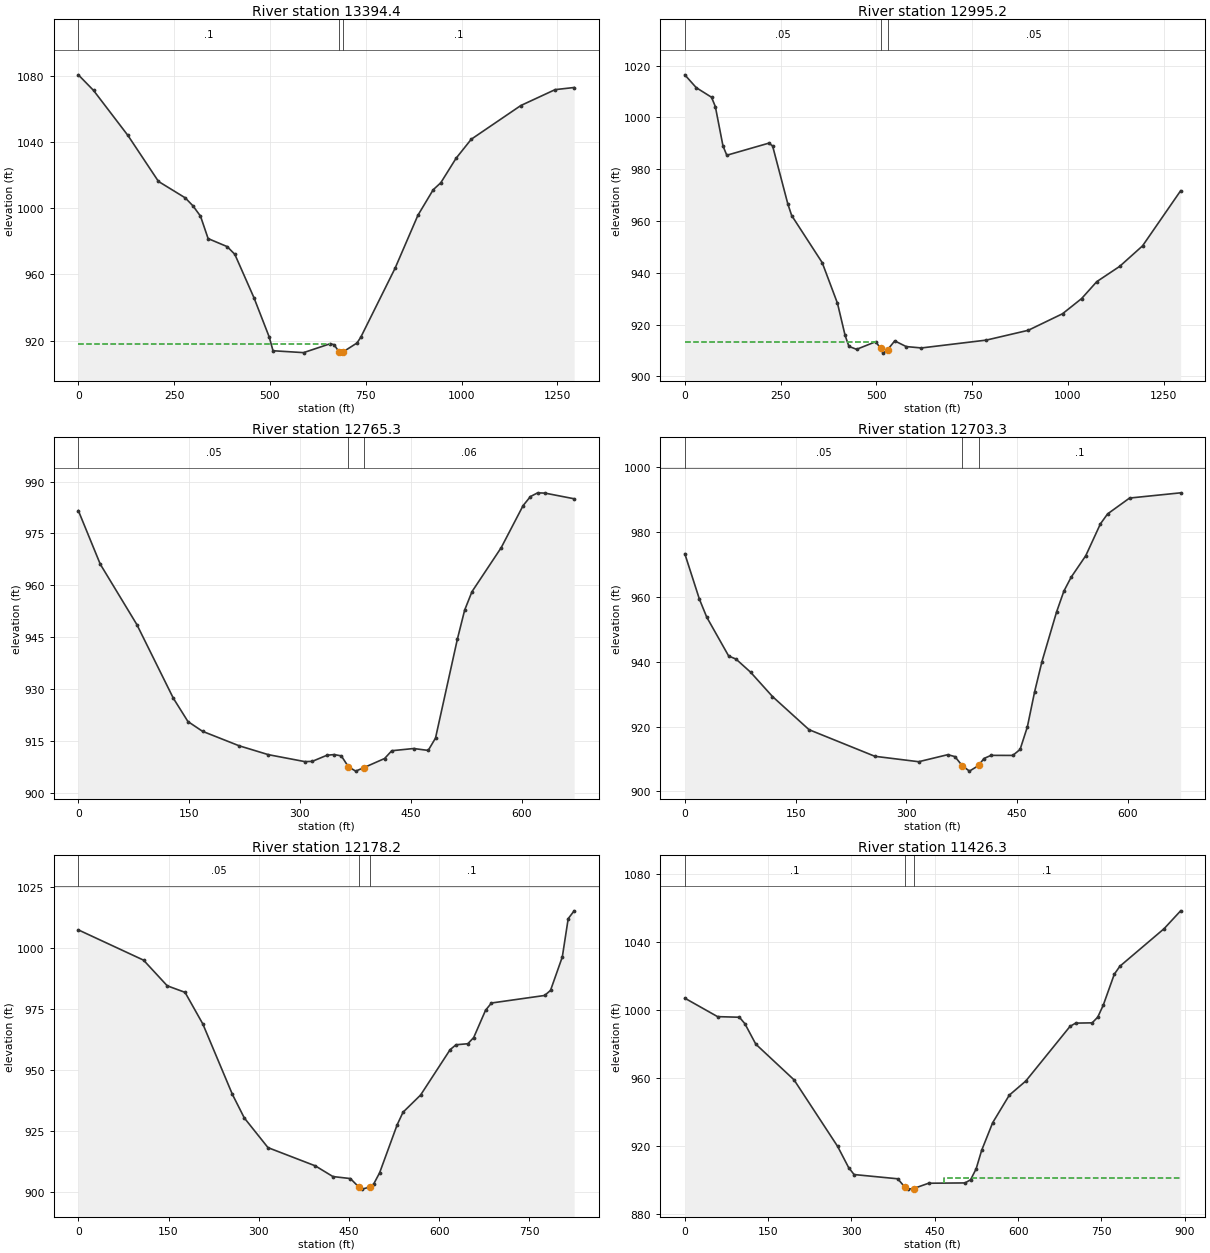
Type RM Length L Ch R = 1 ,13394.4 ,399.1,399.1,399.2
XS GIS Cut Line= 3
     1828832.822      438649.406     1828255.805      438240.341
     1827767.636      437914.878
#Sta/Elev= 30
       0  1080.6    39.8 1071.15   129.5 1043.94   209.2 1016.17   278.9 1006.28
   298.9  1001.5   318.8  995.23   338.7  981.65   388.5   976.8   408.4  972.15
   458.3  945.95   498.1  922.23   508.1  913.88   587.8  912.74   657.5  918.13
   667.5  917.53     680  913.35   687.4  912.44  691.89  913.33   727.2  918.56
   737.1  922.03   826.6  963.72   886.3  995.77   926.1 1011.15     946  1015.4
   985.8 1030.18  1025.5 1041.69  1154.8 1062.05  1244.3 1071.65    1294 1072.94
#Mann= 3 , 0 , 0
       0      .1       0     680    .045       0  691.89      .1       0
#XS Ineff= 2 , 0
          657.51  918.13
Permanent Ineff=
       F       F
Bank Sta=680,691.89
XS Rating Curve= 0 ,0
Exp/Cntr=0.3,0.1

Type RM Length L Ch R = 1 ,12995.2 ,224,229.9,235.6
XS GIS Cut Line= 3
     1828922.406      438224.233     1828345.388      437815.168
     1827857.219      437489.704
#Sta/Elev= 30
       0 1016.47    29.9 1011.51    69.7 1007.82    79.7 1004.21    99.6  989.04
   109.6  985.41   219.2  990.08   229.1  989.03     269  966.55   278.9  962.14
   358.6  943.94   398.5  928.22   418.4  915.81   428.4  911.59   448.3  910.46
   498.1  913.39  511.02  910.88     518  908.99   529.4  910.34   547.9  913.72
   577.8  911.52   617.6  910.99   786.9  914.02   896.2   917.8   985.8   924.2
  1035.5  930.05  1075.2   936.6  1134.9  942.49  1194.6  950.41    1294   971.7
#Mann= 3 , 0 , 0
       0     .05       0  511.02    .045       0   529.4     .05       0
#XS Ineff= 2 , 0
          498.12  913.39  548.09          913.68
Permanent Ineff=
       F       F
Bank Sta=511.02,529.4
XS Rating Curve= 0 ,0
Exp/Cntr=0.3,0.1

Type RM Length L Ch R = 1 ,12765.3 ,62.3,62,61.7
XS GIS Cut Line= 4
     1828856.568      438028.116     1828650.405      437762.274
     1828586.386      437688.489     1828411.907      437527.899
#Sta/Elev= 30
       0  981.61    29.7  966.11    79.2  948.65   128.6  927.34   148.4  920.59
   168.2  917.76   217.7  913.58   257.3  911.01   306.7     909   316.6  909.07
   336.4  910.83   346.2  911.04     356  910.66   365.7  907.48   375.5  906.25
   386.1  907.22   414.6   909.9   424.3  912.15   453.9  912.79   473.6  912.24
   483.5   915.8   513.2  944.51     523  952.85   532.9  958.17   572.4  970.88
   602.1  983.06     612  985.67   621.8  986.75   631.7  986.67   671.2  985.03
#Mann= 3 , 0 , 0
       0     .05       0   365.7    .045       0   386.1     .06       0
Bank Sta=365.7,386.1
XS Rating Curve= 0 ,0
Exp/Cntr=0.3,0.1

Type RM Length L Ch R = 1 ,12703.3 ,516.4,525.1,533.7
XS GIS Cut Line= 4
     1828903.443      437990.356      1828697.28      437724.514
     1828633.261      437650.729     1828458.782      437490.139
#Sta/Elev= 30
       0  973.27    19.8  959.25    29.7  953.72    59.4  941.74    69.3   940.8
      89  936.77   118.7  929.26   168.2  919.04   257.3  910.84   316.6  909.17
     356  911.34   365.7  910.74   375.5  907.97   385.3  906.27     398  908.04
   404.8  910.15   414.6  911.13     444  911.11   453.9  912.96   463.7  919.88
   473.6  930.77   483.5  940.04   503.3  955.34   513.2  961.76     523  966.03
   542.8  972.66   562.6  982.46   572.4  985.55   602.1  990.42   671.2  992.03
#Mann= 3 , 0 , 0
       0     .05       0   375.5    .045       0     398      .1       0
Bank Sta=375.5,398
XS Rating Curve= 0 ,0
Exp/Cntr=0.3,0.1

Type RM Length L Ch R = 1 ,12178.2 ,765.2,751.9,737.9
XS GIS Cut Line= 4
     1829317.072      438036.796     1829195.544      437672.213
      1829132.61      437498.602     1829054.485      437255.546
#Sta/Elev= 30
       0 1007.43   108.4  995.02   147.8   984.5   177.4  981.81   206.9  968.88
   256.2  939.94   275.9  930.32   315.3  918.14     394  910.66   423.2  906.28
   452.3  905.45  467.06   901.8   471.6  901.12  484.24  901.94   491.2   903.3
   500.9  907.83   530.1  927.53   539.8  932.66     569   939.7   618.1  958.31
   627.9  960.32   647.5  960.74   657.3  963.28     677  974.47   686.8  977.44
   775.2  980.53     785  982.62   804.6  996.33   814.4 1012.04   824.3 1015.24
#Mann= 3 , 0 , 0
       0     .05       0  467.06    .045       0  484.24      .1       0
Bank Sta=467.06,484.24
XS Rating Curve= 0 ,0
Exp/Cntr=0.3,0.1

Type RM Length L Ch R = 1 ,11426.3 ,796.4,808.2,819.4
XS GIS Cut Line= 4
     1830003.487      437312.404     1829687.515       437095.39
     1829597.146      437030.595     1829272.584      436800.251
#Sta/Elev= 30
       0 1006.86      59  995.99    98.3  995.63   108.1  991.86   127.8   979.8
   196.6  958.81   275.2  919.58   294.9  907.18   304.7  903.07   383.3  900.57
   396.7  895.45   401.8  894.49   411.7  894.82   438.9  897.96   504.5  898.14
   514.4     900   524.4   906.4   534.3  917.27   554.2  933.59   584.1  949.79
   613.9  958.13   693.5  990.28   703.5  992.17   733.3  992.34   743.3  995.69
   753.2  1002.7   773.1 1020.94   783.1 1025.63   862.7 1047.73   892.5 1058.25
#Mann= 3 , 0 , 0
       0      .1       0   396.7    .045       0   411.7      .1       0
#XS Ineff= 2 , 0
                          465.88          900.98
Permanent Ineff=
       F       F
Bank Sta=396.7,411.7
XS Rating Curve= 0 ,0
Exp/Cntr=0.3,0.1

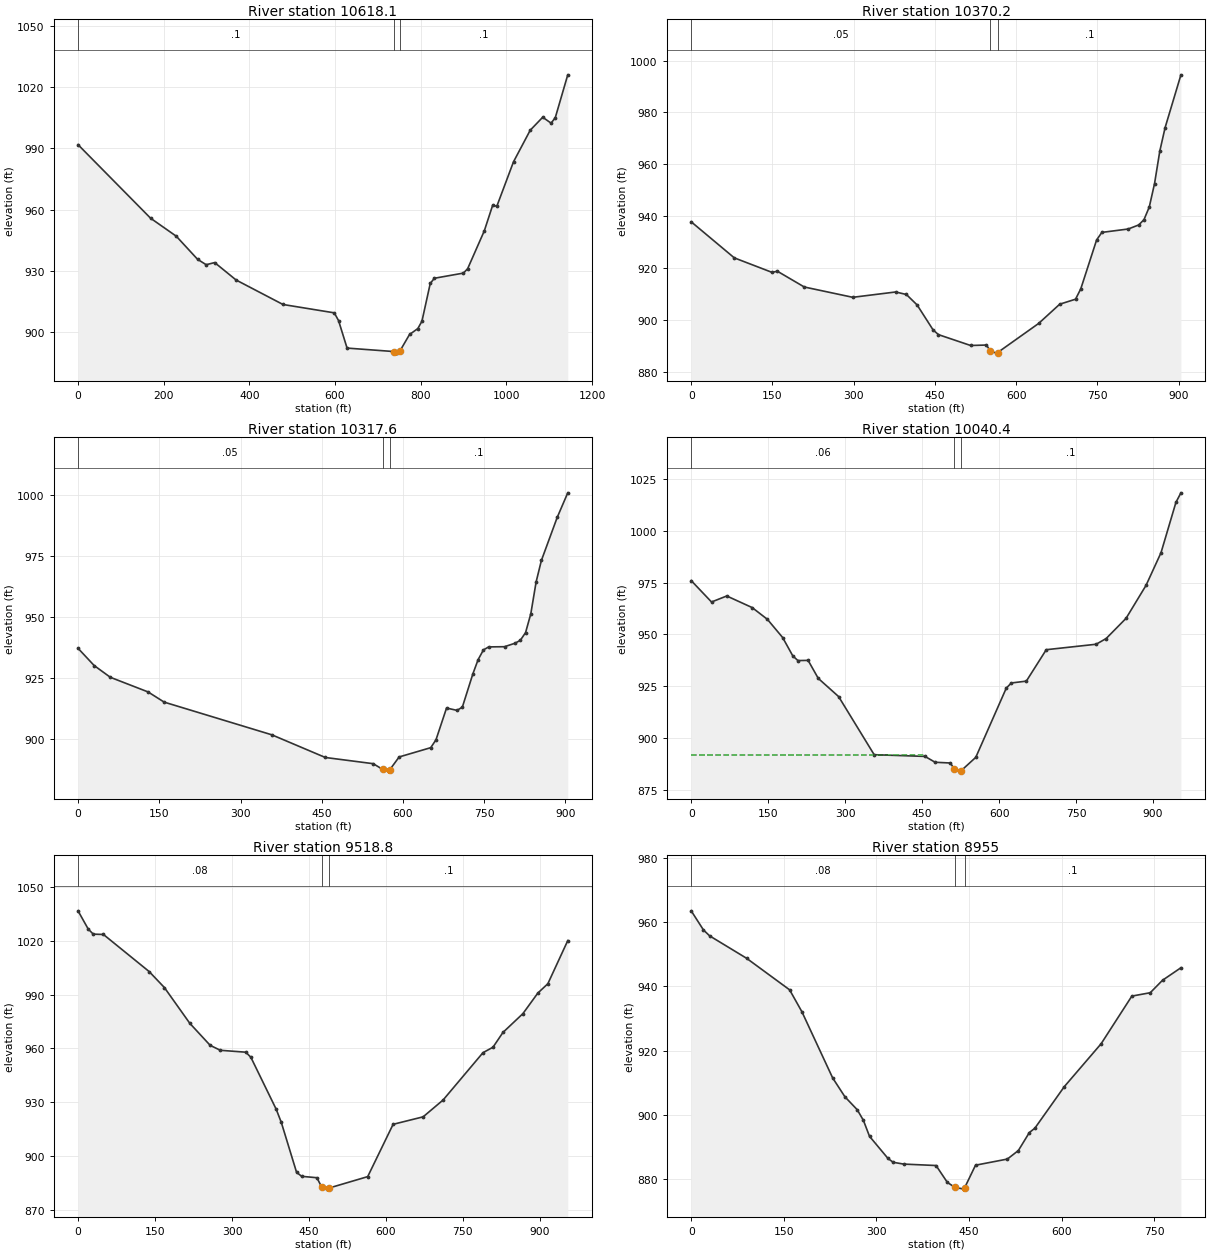
Type RM Length L Ch R = 1 ,10618.1 ,243,247.9,252.5
XS GIS Cut Line= 4
     1830337.037      437118.828     1830130.874      436493.828
     1830033.218      436305.026     1829889.989      436072.821
#Sta/Elev= 30
       0  991.82   169.5  955.77   229.4  946.97   279.2  935.64   299.2     933
   319.1  934.05     369  925.52   478.6  913.51   598.3  909.42   608.3  905.63
   628.2  892.15     737  890.46   745.1  889.68     752  890.86   774.1  898.83
   793.4   901.7     803  905.31   822.4   923.8     832  926.36   899.9   928.9
   909.7  931.03   948.6  949.58   968.1  962.09   977.9  961.66  1016.8  983.42
  1055.8  998.88    1085 1005.26  1104.5 1002.37  1114.3    1005  1143.5 1026.04
#Mann= 3 , 0 , 0
       0      .1       0     737    .045       0     752      .1       0
Bank Sta=737,752
XS Rating Curve= 0 ,0
Exp/Cntr=0.3,0.1

Type RM Length L Ch R = 1 ,10370.2 ,52.5,52.6,52.9
XS GIS Cut Line= 5
     1830528.009      436944.891     1830403.009      436641.506
     1830340.509      436454.006     1830320.978      436379.787
     1830188.166      436108.954
#Sta/Elev= 30
       0  937.78    79.6  923.86   149.2  918.27   159.1  918.71   208.8  912.62
   298.3  908.64   377.5   910.7   397.3  909.73   417.1   905.7   446.7  896.04
   456.6  894.23   515.9  890.05     545  890.22   552.6  887.89   564.1   887.1
   565.9  887.34   641.4  898.54   680.4  905.98   709.6  907.91   719.3  911.91
   748.5  930.76   758.2  933.69   806.9     935   826.3  936.57     836  938.61
   845.8  943.52   855.5  952.55   865.2  965.08     875  974.14   904.2   994.5
#Mann= 3 , 0 , 0
       0     .05       0   552.6    .045       0   565.9      .1       0
Bank Sta=552.6,565.9
XS Rating Curve= 0 ,0
Exp/Cntr=0.3,0.1

Type RM Length L Ch R = 1 ,10317.6 ,276.8,277.2,277.5
XS GIS Cut Line= 5
     1830580.093      436937.079     1830455.093      436633.693
     1830392.593      436446.193     1830373.061      436371.974
     1830240.249      436101.141
#Sta/Elev= 30
       0  937.33    29.8  930.26    59.7  925.44   129.3  919.45   159.1  915.27
   357.8  901.88   456.6  892.59     545  890.05  562.16  887.76   573.7     887
   575.3  887.49   592.9  892.81   651.2  896.61   660.9  899.84   680.4  912.85
   699.8  911.89   709.6  913.24     729  926.85   738.7  932.68   748.5  936.67
   758.2   937.9   787.4  937.98   806.9  939.41   816.6   940.6   826.3  943.76
     836  951.51   845.8  964.54   855.5  973.31   884.7  990.95   904.2 1001.03
#Mann= 3 , 0 , 0
       0     .05       0  562.16    .045       0   575.3      .1       0
Bank Sta=562.16,575.3
XS Rating Curve= 0 ,0
Exp/Cntr=0.3,0.1

Type RM Length L Ch R = 1 ,10040.4 ,528,521.7,512.4
XS GIS Cut Line= 4
     1830777.743      436882.564     1830657.286      436433.014
     1830618.589       436279.41     1830540.862       435958.26
#Sta/Elev= 30
       0  975.97    39.6  965.65    69.3  968.55   118.8  962.96   148.5  957.29
   178.2  948.51     198  939.65     208  937.41   227.8   937.5   247.6  928.82
   287.2  920.06   356.5  892.03   455.5  891.21   475.3  888.38     505  888.03
  512.44  885.17   524.8  884.11   525.4  884.19   554.5  890.76   613.9  924.13
   623.8  926.61     653   927.5   691.8  942.65     789  945.28   808.5  948.03
   847.3  957.78   886.2  973.66   915.4  989.42   944.5 1013.71   954.2 1018.28
#Mann= 3 , 0 , 0
       0     .06       0  512.44    .045       0   525.4      .1       0
#XS Ineff= 2 , 0
          454.73  891.94
Permanent Ineff=
       F       F
Bank Sta=512.44,525.4
XS Rating Curve= 0 ,0
Exp/Cntr=0.3,0.1

Type RM Length L Ch R = 1 ,9518.8  ,515.7,563.7,600
XS GIS Cut Line= 4
     1831302.022      436594.162     1831097.251      436176.222
     1831029.699      436032.945     1830891.583      435732.773
#Sta/Elev= 30
       0 1036.67    19.8 1026.53    29.7 1023.67    49.5 1023.48   138.6  1002.8
   168.3  993.88   217.8  973.94   257.5  961.65   277.3   958.9   326.8  957.84
   336.7  955.03   386.2  925.97   396.1  918.65   425.8  890.86   435.7  888.62
   465.4  887.84   474.4  882.82   485.2  881.48   489.4  882.11   564.4  888.45
   613.9  917.62   672.4  921.79   711.3  931.18     789  957.57   808.5  960.61
   827.9  968.85   866.8  979.34   895.9  990.81   915.4  996.01   954.2 1020.06
#Mann= 3 , 0 , 0
       0     .08       0   474.4    .045       0   489.4      .1       0
Bank Sta=474.4,489.4
XS Rating Curve= 0 ,0
Exp/Cntr=0.3,0.1

Type RM Length L Ch R = 1 ,8955    ,87.7,73.3,88
XS GIS Cut Line= 6
     1831376.534      436279.613     1831463.697      435973.049
     1831490.781      435930.341     1831570.665      435869.695
     1831576.572      435845.742     1831404.098       435602.78
#Sta/Elev= 30
       0  963.47    19.9  957.51    29.9  955.68    89.6  948.73   159.4   938.9
   179.3  932.09   229.1  911.51     249  905.63   268.9  901.62   278.9  898.32
   288.8  893.35   318.7  886.47   327.1  885.27     344  884.71   396.6  884.26
   414.9  879.01   427.2  877.46   442.2  876.92  443.01  877.39   460.5  884.36
   512.1  886.27   529.9  888.92   547.7  894.52   556.6  895.86   604.3  908.79
   663.9  922.12   713.7  936.95   743.5     938   763.4  941.88   793.2  945.77
#Mann= 3 , 0 , 0
       0     .08       0   427.2    .045       0  443.01      .1       0
Bank Sta=427.2,443.01
XS Rating Curve= 0 ,0
Exp/Cntr=0.3,0.1

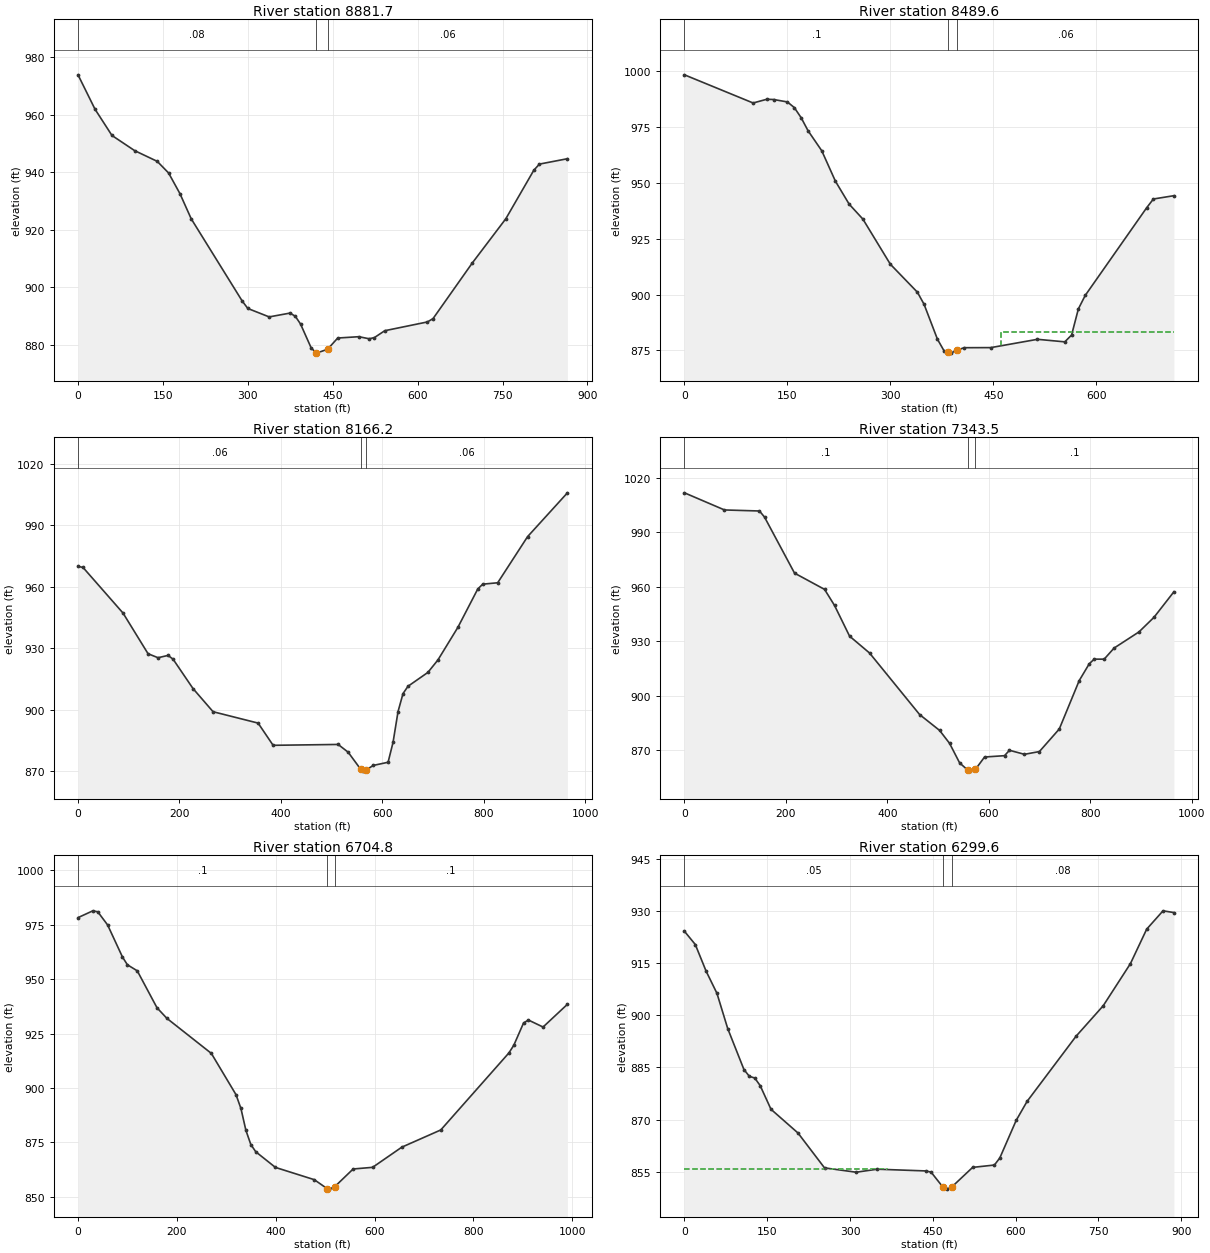
Type RM Length L Ch R = 1 ,8881.7  ,447.6,392.1,318.9
XS GIS Cut Line= 6
     1831444.893      436282.869      1831525.85      435983.639
     1831585.174      435925.429     1831655.885      435863.674
     1831614.167      435772.051     1831450.105       435548.96
#Sta/Elev= 30
       0  973.86      30  961.92      60  952.78     100  947.52     140  943.78
     160  939.75     180  932.59     200  923.81     290  895.26     300  892.65
   337.7  889.72   374.6  891.05   383.9  889.93   393.1  887.25   411.9  878.95
  420.05  877.34   421.3  877.13   440.9  878.48   458.8  882.38   496.1  882.84
   514.4  882.12   523.6  882.53   541.9  884.92   617.3  887.97   627.2  889.13
   696.4  908.43   755.8  923.85   805.2  940.69   815.1  942.83   864.6   944.7
#Mann= 3 , 0 , 0
       0     .08       0  420.05    .045       0   440.9     .06       0
Bank Sta=420.05,440.9
XS Rating Curve= 0 ,0
Exp/Cntr=0.3,0.1

Type RM Length L Ch R = 1 ,8489.6  ,313.6,323.5,330.5
XS GIS Cut Line= 4
     1832072.588       435828.64     1831856.355      435592.797
     1831664.298      435562.415       1831467.9      435532.033
#Sta/Elev= 30
       0  998.49     100  985.88     120  987.54     130  987.43     150  986.34
     160  983.83     170  979.29     180  973.48     200   964.5     220  950.81
     240  940.54     260  933.85     300  913.64   339.4  901.11   349.1  895.72
   368.6  880.06   378.3  874.81   384.3  874.19     388  873.81   397.7   875.2
   407.5  876.24   446.4  876.28   514.4     880   554.2  878.86   564.1  881.91
     574  893.63     584  899.67   673.4  938.88   683.3  942.86   713.2  944.34
#Mann= 3 , 0 , 0
       0      .1       0   384.3    .045       0   397.7     .06       0
#XS Ineff= 2 , 0
                           460.6          883.14
Permanent Ineff=
       F       F
Bank Sta=384.3,397.7
XS Rating Curve= 0 ,0
Exp/Cntr=0.3,0.1

Type RM Length L Ch R = 1 ,8166.2  ,820.6,822.7,826.3
XS GIS Cut Line= 3
     1832304.777      435532.091     1831802.172      435258.899
     1831447.169      435090.467
#Sta/Elev= 30
       0  970.06     9.9  969.52    88.8  947.25   138.1  927.42   157.8  925.47
   177.5   926.6   187.4  924.77   226.8  910.41   266.3  899.12   355.1  893.57
   384.7  882.73   512.9  883.15   532.6  879.38   557.7  870.93   562.2  870.13
   567.9  870.62   581.9   872.9   611.4  874.46   621.2  884.22     631  899.19
   640.8  907.96   650.6  911.53   689.9  918.31   709.6  924.36   748.9  940.25
   788.2  959.01     798  961.37   827.5  962.05   886.4  984.55     965 1005.94
#Mann= 3 , 0 , 0
       0     .06       0   557.7    .045       0   567.9     .06       0
Bank Sta=557.7,567.9
XS Rating Curve= 0 ,0
Exp/Cntr=0.3,0.1

Type RM Length L Ch R = 1 ,7343.5  ,648,638.7,629.6
XS GIS Cut Line= 3
     1832768.768      434994.873     1832322.622      434636.825
     1832003.143      434408.067
#Sta/Elev= 30
       0 1011.67    78.9 1002.24   147.9 1001.67   157.8  998.33     217  967.47
   276.2  958.52   295.9  949.66   325.5  932.79   364.9   923.5   463.6  889.63
     503   880.9   522.7  873.77   542.5  863.02   558.5  859.06   562.2  858.48
   573.5  859.39   591.7  866.25     631  866.98   640.8  869.95   670.3  867.74
   699.8  869.25     739  881.66   778.3  908.31     798  917.52   807.8  920.13
   827.5  920.11   847.1  926.22   896.2  935.12   925.7  943.13     965   957.2
#Mann= 3 , 0 , 0
       0      .1       0   558.5    .045       0   573.5      .1       0
Bank Sta=558.5,573.5
XS Rating Curve= 0 ,0
Exp/Cntr=0.3,0.1

Type RM Length L Ch R = 1 ,6704.8  ,438.4,405.2,372.7
XS GIS Cut Line= 4
     1833161.421      434355.254     1832786.421      434249.785
     1832614.546      434208.119     1832192.379       434172.39
#Sta/Elev= 30
       0  978.25      30  981.37      40  980.92    59.9  974.88    89.9  960.17
    99.9   956.6   119.9   953.8   159.8  936.84   179.8  931.99   269.7   915.9
   319.6  896.95   329.6  890.59   339.6  880.58   349.6  874.04   359.6  870.71
   399.4  863.52     478  857.89   503.9  853.79   507.4  853.55   518.9  854.57
   556.6   862.8     596  863.56   655.1  872.83   733.9  880.73   871.8  916.13
   881.7  919.67   901.4   929.9   911.2  931.21   940.8     928   990.1  938.45
#Mann= 3 , 0 , 0
       0      .1       0   503.9    .045       0   518.9      .1       0
Bank Sta=503.9,518.9
XS Rating Curve= 0 ,0
Exp/Cntr=0.3,0.1

Type RM Length L Ch R = 1 ,6299.6  ,58.7,56.1,56.2
XS GIS Cut Line= 6
      1833057.57      433867.971     1832847.501      433820.228
     1832655.053      433805.203     1832608.178      433908.067
      1832490.99      433980.984     1832279.185      434061.279
#Sta/Elev= 30
       0  924.21    19.6  920.41    39.2  912.73    58.8  906.36    78.3  896.22
   107.7  884.41   117.5  882.45   127.3  881.96   137.1  879.78   156.7  872.96
   205.6  866.13   253.7  856.08     311  854.83   349.3   855.7   437.2   855.2
   446.7  854.86   468.5  850.48   474.9  849.96   484.3  850.59     522  856.22
   561.5   856.9   571.3  858.96   600.9  869.76   620.6  875.22   709.3  893.98
   758.5  902.76   807.8  914.89   837.3  924.83   866.9  930.11   886.6  929.61
#Mann= 3 , 0 , 0
       0     .05       0   468.5    .045       0   484.3     .08       0
#XS Ineff= 2 , 0
          367.51  855.62
Permanent Ineff=
       F       F
Bank Sta=468.5,484.3
XS Rating Curve= 0 ,0
Exp/Cntr=0.3,0.1

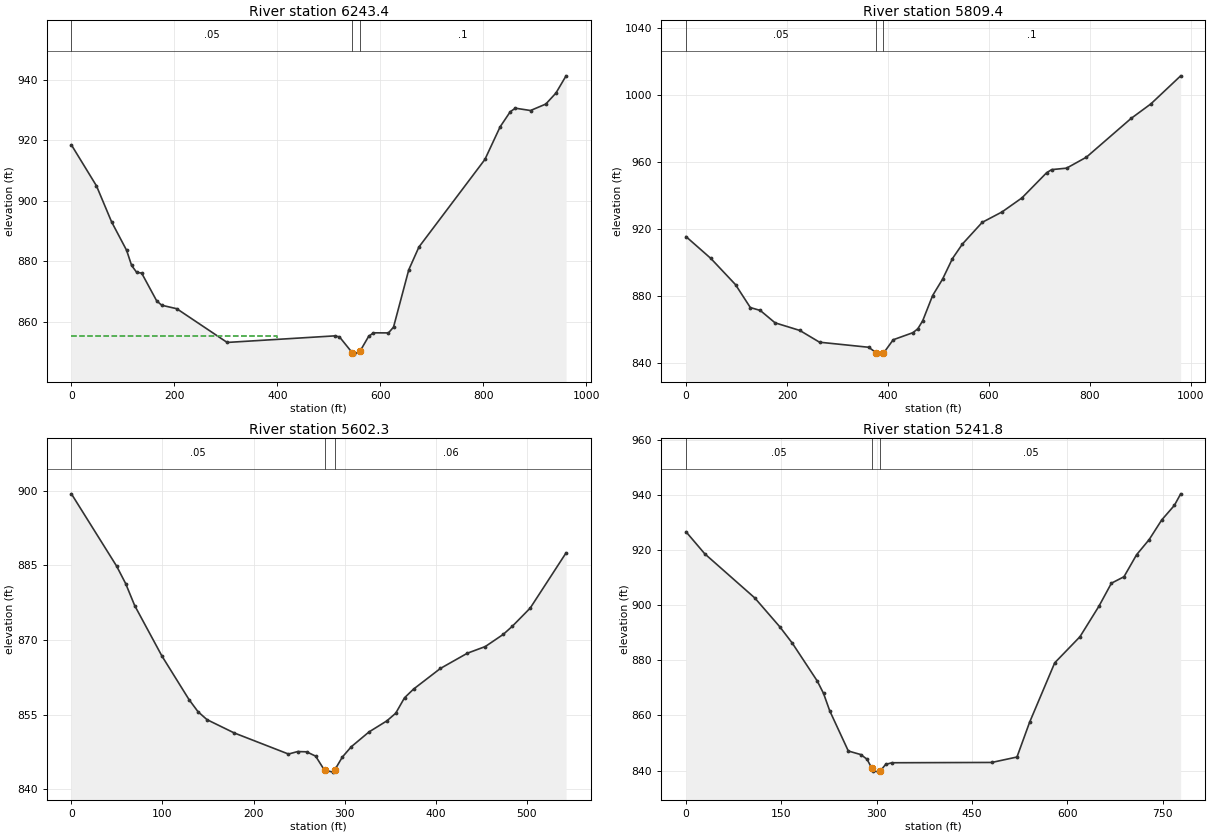
Type RM Length L Ch R = 1 ,6243.4  ,383.5,434,481.9
XS GIS Cut Line= 6
     1833095.765      433820.228      1832838.82      433763.804
     1832619.897       433759.63     1832573.022      433862.495
     1832455.834      433935.411     1832244.029      434015.706
#Sta/Elev= 30
       0  918.45    48.7  904.91      78  893.04   107.2  883.62   116.9  878.62
   126.7  876.35   136.4   876.1   165.6  866.92   175.4  865.48   204.6  864.33
   302.4  853.19   511.1  855.36   520.5  855.02   545.5  849.75   548.8  849.33
   560.5  850.33     577  855.17   586.4  856.37   615.6  856.34   625.4  858.25
     655  877.19   674.7  884.71   802.8  913.64   832.4  924.43     852   929.4
   861.9  930.58   891.4  929.81     921  931.94   940.7  935.57   960.4  941.27
#Mann= 3 , 0 , 0
       0     .05       0   545.5    .045       0   560.5      .1       0
#XS Ineff= 2 , 0
          399.31  855.42
Permanent Ineff=
       F       F
Bank Sta=545.5,560.5
XS Rating Curve= 0 ,0
Exp/Cntr=0.3,0.1

Type RM Length L Ch R = 1 ,5809.4  ,206.8,207.1,207.4
XS GIS Cut Line= 4
     1833123.542      433803.084     1832897.848      433736.895
     1832758.959      433549.177      1832373.76      433213.609
#Sta/Elev= 30
       0  915.59      49   902.6      98  886.91   127.4   873.2     147  871.49
   176.4  864.08   225.4  859.53   264.4  852.51   361.7  849.49   376.8  846.19
   381.1  845.39   390.9  845.91   410.3  853.97   449.2  858.19     459  860.51
   468.7  865.31   488.4  880.41     508  890.15   527.7   902.5   547.3  911.13
   586.6  924.11   625.9  930.34   665.2   938.7   714.3   953.8   724.2  955.61
   753.6  956.47   792.9  963.04   881.3  986.16   920.6  994.87   979.6 1011.63
#Mann= 3 , 0 , 0
       0     .05       0   376.8    .045       0   390.9      .1       0
Bank Sta=376.8,390.9
XS Rating Curve= 0 ,0
Exp/Cntr=0.3,0.1

Type RM Length L Ch R = 1 ,5602.3  ,368.6,360.5,352.4
XS GIS Cut Line= 4
     1833162.605      433754.907     1833003.751      433538.761
     1832946.459      433459.768     1832819.723      433335.636
#Sta/Elev= 30
       0  899.37    49.7  884.84    59.6  881.34    69.5  876.93    99.4   866.8
   129.2  858.04   139.1   855.6     149  854.01   178.8  851.35   238.4  847.11
   248.4  847.61   258.3  847.56   268.2  846.69     278  843.84   287.8  843.48
  289.16  843.91   297.5   846.5   307.3  848.57   326.8  851.55   346.3  853.76
   356.1   855.3   365.8  858.41   375.7  860.15   405.2   864.3   434.8  867.36
   454.5   868.7   474.2  871.14   484.1  872.76   503.8  876.42   543.2  887.51
#Mann= 3 , 0 , 0
       0     .05       0     278    .045       0  289.16     .06       0
Bank Sta=278,289.16
XS Rating Curve= 0 ,0
Exp/Cntr=0.3,0.1

Type RM Length L Ch R = 1 ,5241.8  ,230.8,224.5,218.2
XS GIS Cut Line= 4
     1833467.553      433525.689     1833340.817      433350.342
     1833177.622      433242.703     1832876.147      433034.269
#Sta/Elev= 30
       0  926.59    29.5   918.6   108.2   902.6   147.5  892.15   167.2  886.22
   206.5  872.48   216.4  867.98   226.1  861.69   255.4  847.09     275   845.8
   284.8  844.12   292.6  840.75   294.6  839.89   304.3  839.43  305.24  839.73
   314.1  842.22   323.9  842.83   481.2  842.94   520.8  844.91   540.6  857.48
   580.2  879.07   619.9  888.53   649.6  899.54   669.4  907.94   689.2  910.29
     709  918.26   728.8  923.76   748.6  930.89   768.5  936.17   778.4  940.35
#Mann= 3 , 0 , 0
       0     .05       0   292.6    .045       0  305.24     .05       0
Bank Sta=292.6,305.24
XS Rating Curve= 0 ,0
Exp/Cntr=0.3,0.1