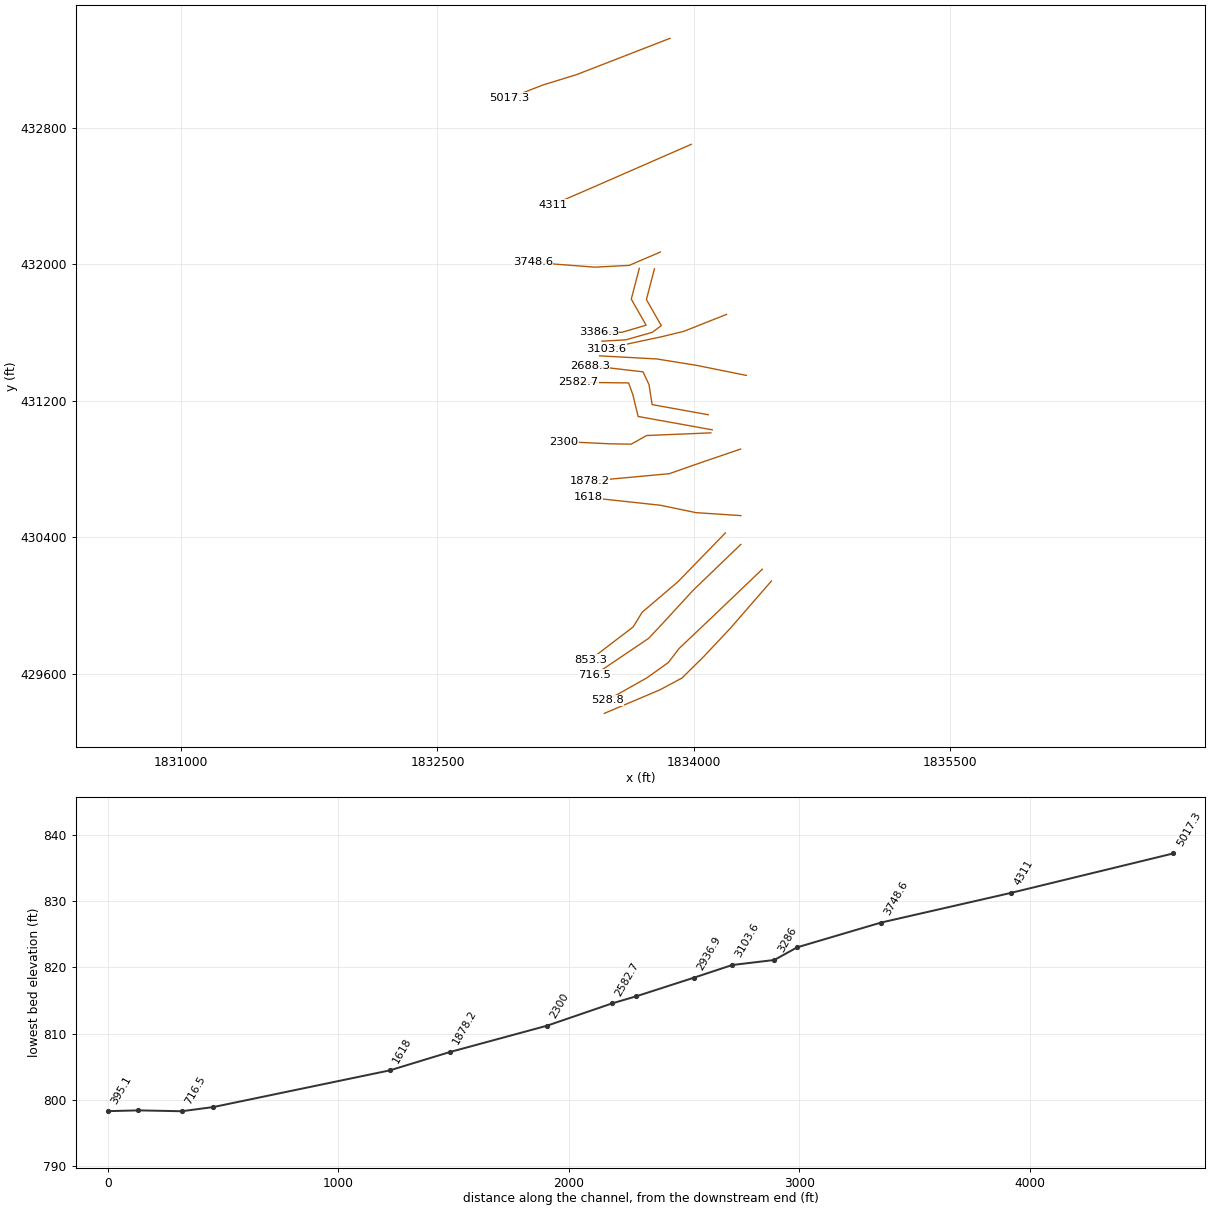
HEC-RAS study RobnsnRn.prj: RobnsnRn

--- RobnsnRn.g01 (geometry) --- (continued)

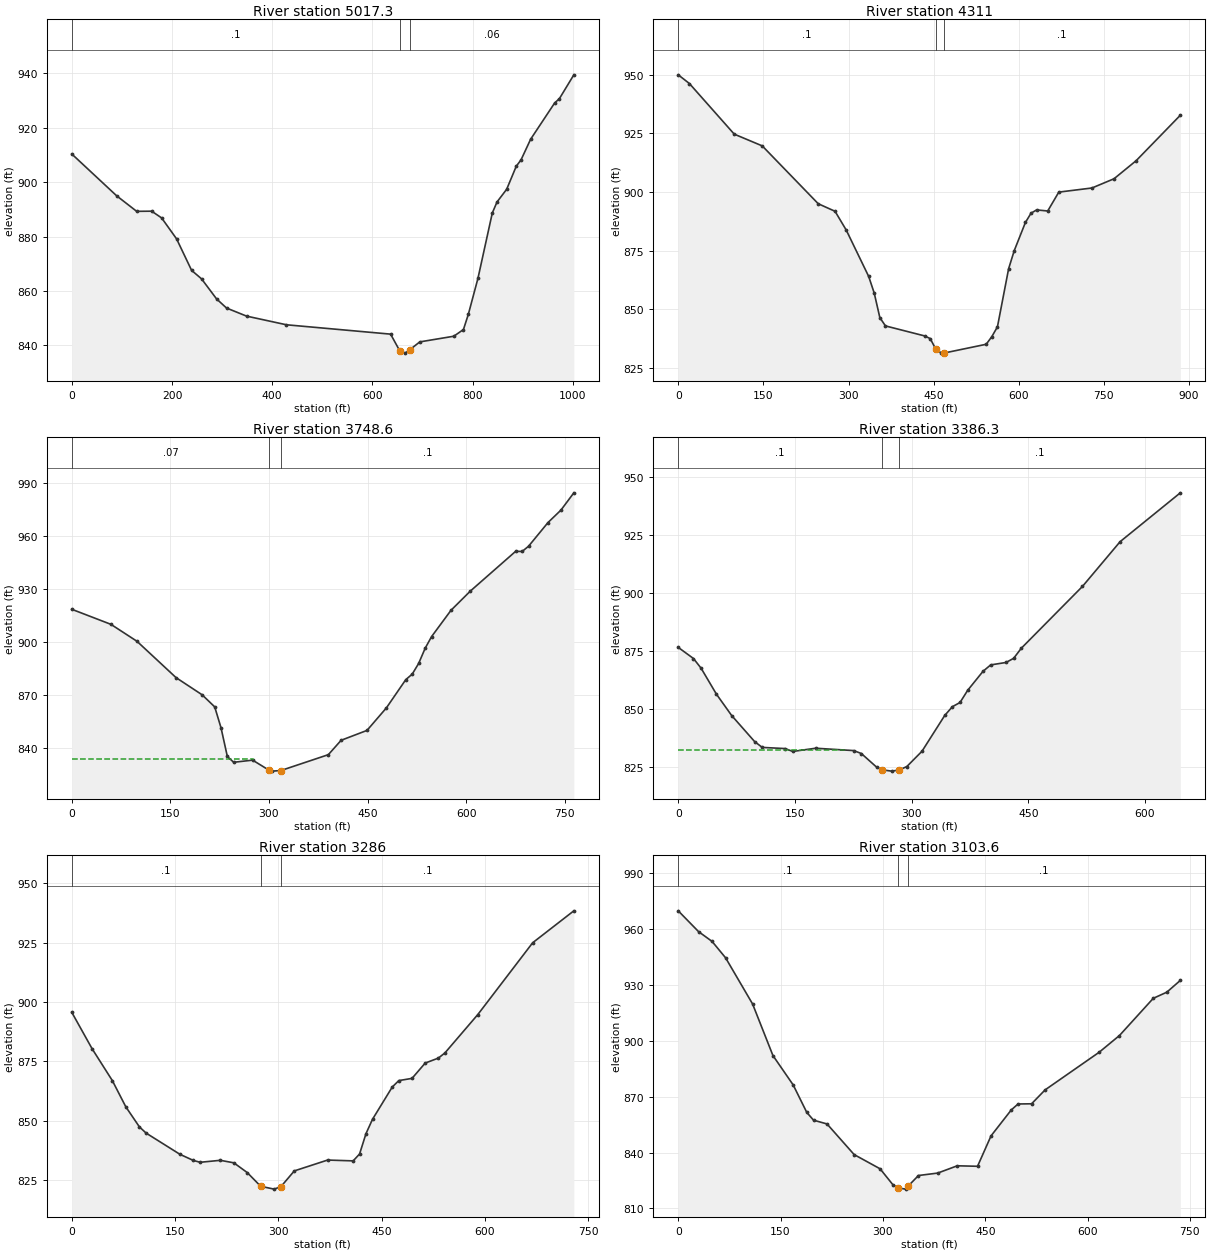
Type RM Length L Ch R = 1 ,5017.3  ,703.5,706.2,708.8
XS GIS Cut Line= 4
     1833860.821      433325.588     1833313.078      433112.394
     1833118.634      433052.498     1832922.453      432976.109
#Sta/Elev= 30
       0   910.4    89.7     895   129.5  889.31   159.4  889.37   179.3  886.89
   209.2  879.17   239.1  867.61     259  864.48   288.9  857.12   308.8  853.76
   348.7  850.79   428.4   847.6   636.2  844.16   654.6  837.96   665.3  837.18
     675  838.51   694.4  841.31   762.2  843.39   781.5  845.85   791.2  851.39
   810.4  864.63   839.1  888.71   848.6  892.78   867.8  897.43   886.9  905.89
   896.5  908.26   915.6  915.83   963.5  929.15     973  930.75  1001.8   939.5
#Mann= 3 , 0 , 0
       0      .1       0   654.6    .045       0     675     .06       0
Bank Sta=654.6,675
XS Rating Curve= 0 ,0
Exp/Cntr=0.3,0.1

Type RM Length L Ch R = 1 ,4311    ,570.5,562.5,554.4
XS GIS Cut Line= 3
     1833985.033      432704.129     1833397.602      432446.821
     1833174.399       432349.96
#Sta/Elev= 30
       0  950.04    19.7  946.32    98.7  924.71     148   919.7   246.7  894.99
   276.3  891.77     296  883.75   335.5  863.98   345.3  856.87   355.2  846.38
   365.1  842.83   434.1  838.56     444  837.41   453.4  833.06   463.7  831.21
   468.4  831.25   542.6  834.99   552.5  838.25   562.4  842.43   582.1  867.25
     592  874.97   611.7  887.01   621.6  890.96   631.4  892.36     651   891.9
   670.5  899.96   728.9  901.72   767.8  905.66   806.8  913.38   884.6  932.78
#Mann= 3 , 0 , 0
       0      .1       0   453.4    .045       0   468.4      .1       0
Bank Sta=453.4,468.4
XS Rating Curve= 0 ,0
Exp/Cntr=0.3,0.1

Type RM Length L Ch R = 1 ,3748.6  ,311.3,362.3,413.4
XS GIS Cut Line= 4
     1833804.358      432072.564     1833622.067      431994.439
     1833420.678      431984.022     1833057.831        432011.8
#Sta/Elev= 30
       0  918.55    59.5  910.02    99.2   900.4   158.7  879.77   198.3  870.05
   217.5  863.18   227.1  851.29   236.7  835.06   246.3  831.76   275.2  832.97
  300.26  827.24     304  826.74   317.9  827.04   390.4  836.08   409.8  844.23
   449.2  849.84   478.7  862.62   508.2  878.64     518  881.77   527.8  887.84
   537.7  896.46   547.5  903.08     577  917.98   606.5   928.9   675.4  951.44
   685.2  951.34     695  954.32   724.6  967.76   744.2  974.78   763.9  984.61
#Mann= 3 , 0 , 0
       0     .07       0  300.26    .045       0   317.9      .1       0
#XS Ineff= 2 , 0
          275.52  833.58
Permanent Ineff=
       F       F
Bank Sta=300.26,317.9
XS Rating Curve= 0 ,0
Exp/Cntr=0.3,0.1

Type RM Length L Ch R = 1 ,3386.3  ,102,100.3,97.5
XS GIS Cut Line= 5
     1833681.095      431977.078      1833634.22      431796.522
     1833721.025      431643.745     1833579.272      431601.977
     1833443.855      431603.279
#Sta/Elev= 30
       0   876.4    19.6  871.59    29.4  867.41    49.1  856.22    68.7     847
    98.2  835.77     108  833.25   137.4  832.75   147.3  831.51   176.7   832.9
   225.6  831.88   235.4  830.62   254.9  824.78   261.7   823.6   274.4  823.02
   284.2  823.51   293.9     825   313.4   831.6   342.7  847.07   352.5  850.82
   362.3  852.63   372.1  857.87   391.8  866.06   401.7  868.84   421.4  869.89
   431.2  871.67   441.1  876.04   519.7   902.7   568.1     922   645.5  943.07
#Mann= 3 , 0 , 0
       0      .1       0   261.7    .045       0   284.2      .1       0
#XS Ineff= 2 , 0
          215.01  832.32
Permanent Ineff=
       F       F
Bank Sta=261.7,284.2
XS Rating Curve= 0 ,0
Exp/Cntr=0.3,0.1

Type RM Length L Ch R = 1 ,3286    ,227.6,182.4,138.1
XS GIS Cut Line= 6
     1833769.636      431974.474     1833722.761      431793.918
     1833809.567       431641.14     1833757.657      431601.977
     1833601.407      431557.706     1833462.084      431549.894
#Sta/Elev= 30
       0  895.66    29.4  880.35    58.9  866.87    78.5   855.8    98.2  847.36
     108  844.72   157.1  835.78   176.7  833.18   186.5  832.42   215.8  833.25
   235.4  832.19   254.9  828.07   274.4  822.29   293.9   821.1   303.7  822.12
   323.2  828.78   371.6  833.36   408.7  833.01     418  835.92   427.3  844.49
   436.8  850.56   465.5  864.17     475  866.86   494.2   867.8   513.3  874.25
   532.4  876.34   541.9  878.51   589.7   894.7   669.4  924.98   729.2  938.44
#Mann= 3 , 0 , 0
       0      .1       0   274.4    .045       0   303.7      .1       0
Bank Sta=274.4,303.7
XS Rating Curve= 0 ,0
Exp/Cntr=0.3,0.1

Type RM Length L Ch R = 1 ,3103.6  ,175.8,166.7,157.8
XS GIS Cut Line= 4
     1834191.251      431707.012     1833942.553      431608.053
     1833814.949      431576.803     1833485.522      431506.491
#Sta/Elev= 30
       0   969.8    29.7  958.66    49.6  953.37    69.4  944.57     109  919.76
   138.8  892.08   168.5  876.29   188.4  861.54   198.3  857.37   218.1  855.34
   257.8   838.9   295.8  831.27   314.6  822.72   321.8     821   333.4  820.34
   336.8   821.9   352.1  827.65   380.3  828.96     409  832.87   438.7  832.61
   458.5  848.96   488.2  862.89   498.1  866.07   517.9  866.17   537.7  873.63
     617  893.86   646.7  902.83   696.3  922.82   716.1   926.1   735.9  932.43
#Mann= 3 , 0 , 0
       0      .1       0   321.8    .045       0   336.8      .1       0
Bank Sta=321.8,336.8
XS Rating Curve= 0 ,0
Exp/Cntr=0.3,0.1

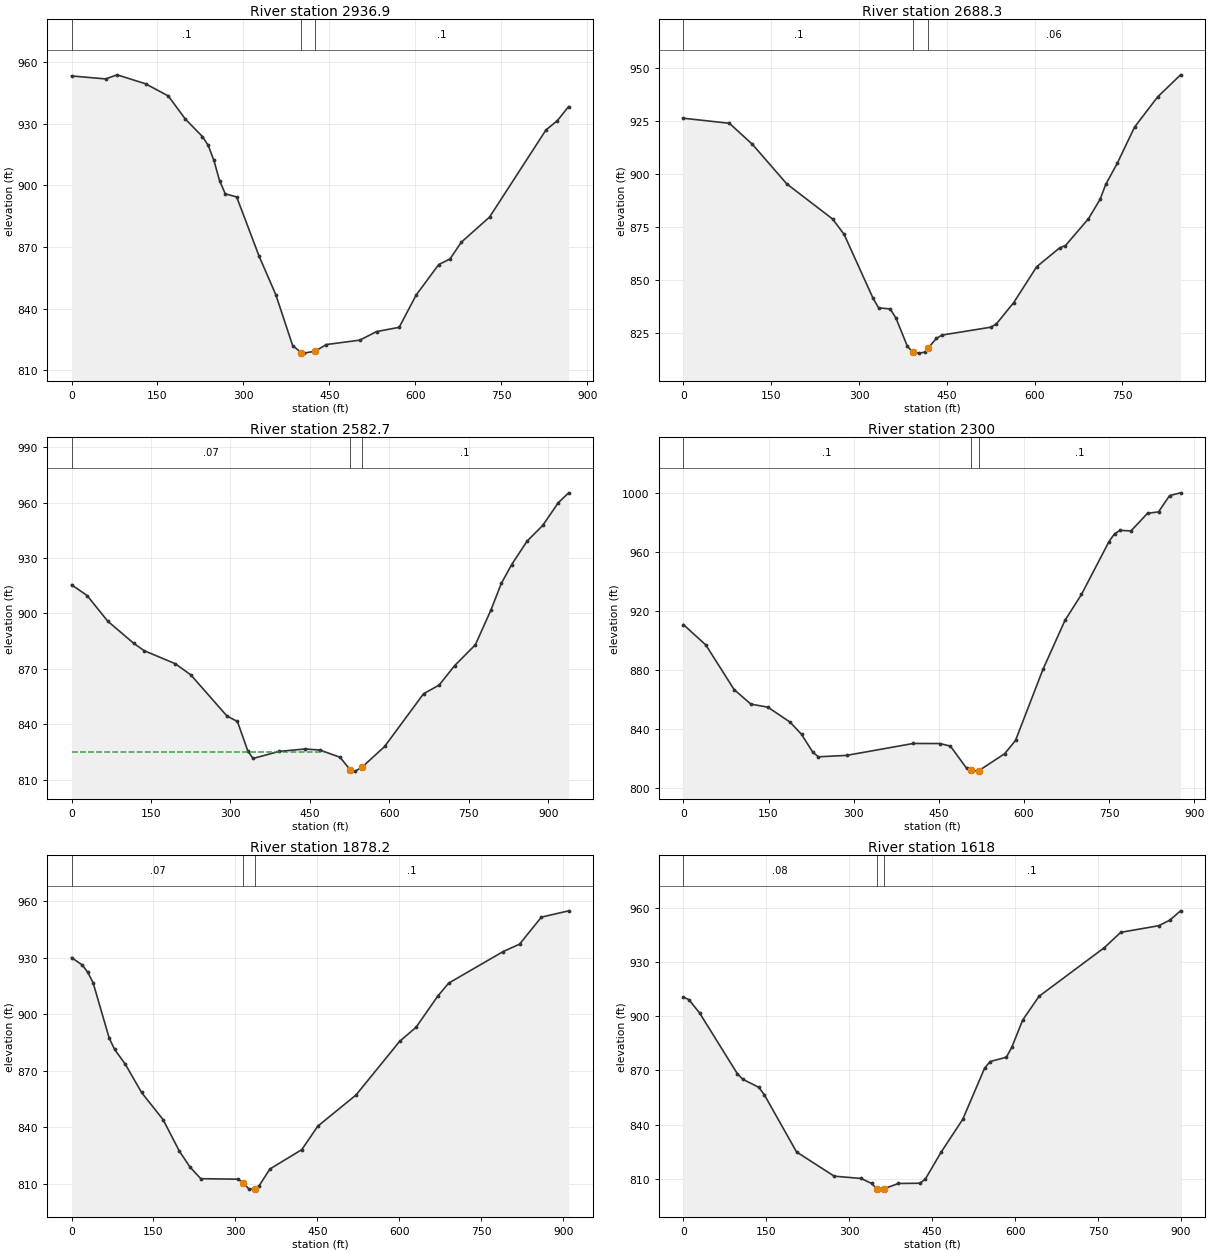
Type RM Length L Ch R = 1 ,2936.9  ,277.3,248.5,219.8
XS GIS Cut Line= 4
     1834307.136      431349.373      1834014.97      431408.501
     1833783.699      431445.727     1833449.063      431463.956
#Sta/Elev= 30
       0  953.12    59.6  951.67    79.5  953.66   129.2  949.31   168.9  943.39
   198.7  932.12   228.5  923.66   238.5   919.4   248.4  912.14   258.3  902.28
   268.3  895.84   288.2  894.31   327.4  865.49   356.6  846.74   385.9  822.08
  401.32  818.55   405.4  818.42     425  819.35   444.5  822.58   503.1  824.74
   532.3  828.89   571.8  830.97   601.3   846.6   640.8  861.48   660.5  864.18
   680.2  872.33   729.5  884.54     828  926.89   847.8  931.39   867.5  938.24
#Mann= 3 , 0 , 0
       0      .1       0  401.32    .045       0     425      .1       0
Bank Sta=401.32,425
XS Rating Curve= 0 ,0
Exp/Cntr=0.3,0.1

Type RM Length L Ch R = 1 ,2688.3  ,104.3,105.6,107.2
XS GIS Cut Line= 5
      1834084.48      431118.904      1833756.29      431178.033
     1833738.061      431294.786      1833702.97      431370.206
      1833390.47      431406.664
#Sta/Elev= 30
       0  926.45    78.5  924.06   117.7  914.19   176.6  895.47     255  878.88
   274.6  871.62   323.7  841.68   333.5  836.96   353.2   836.5     363  832.23
   382.7  818.82   392.6  815.98   402.4  815.63   412.2  816.08   417.9  817.94
     432  822.54   441.8  824.15   525.6  827.89   534.8  829.45   564.3  839.47
   603.6   856.4     643  865.33   652.8  866.39   692.1  879.06   711.8  888.15
   721.6  895.24   741.3  905.22   770.8  922.27   810.1  936.47   849.4  946.93
#Mann= 3 , 0 , 0
       0      .1       0   392.6    .045       0   417.9     .06       0
Bank Sta=392.6,417.9
XS Rating Curve= 0 ,0
Exp/Cntr=0.3,0.1

Type RM Length L Ch R = 1 ,2582.7  ,251.8,282.7,313.4
XS GIS Cut Line= 5
     1834107.917      431030.362     1833674.324      431108.487
     1833643.009      431237.495     1833618.703      431305.203
       1833325.3      431308.675
#Sta/Elev= 30
       0   915.5    29.4  909.66    68.5  895.74   117.5  883.78   137.1   879.8
   195.8  872.74   225.2  866.71   293.7  844.34   313.3  841.45   332.9  825.46
   342.7   821.4   391.6  825.21   440.6  826.54     469  825.98     507  822.06
   525.9  815.38   535.4  814.55     548  816.52   591.3  827.92   664.8  856.48
   694.2  861.17   723.5   871.7   762.6  883.01     792  901.84   811.5  916.18
   831.1  926.41   860.4   939.2   889.8  947.62   919.1  959.93   938.7  965.28
#Mann= 3 , 0 , 0
       0     .07       0   525.9    .045       0     548      .1       0
#XS Ineff= 2 , 0
          477.48  825.14
Permanent Ineff=
       F       F
Bank Sta=525.9,548
XS Rating Curve= 0 ,0
Exp/Cntr=0.3,0.1

Type RM Length L Ch R = 1 ,2300    ,414.8,421.9,428
XS GIS Cut Line= 5
     1834100.006      431012.481     1833723.704      430996.856
      1833633.84      430946.211      1833509.22      430948.324
     1833237.952      430961.344
#Sta/Elev= 30
       0  910.58    39.6  896.69    89.2  866.55   118.9  856.61   148.7  854.58
   188.3  844.31   208.1  836.11     228  823.97   237.9   820.9   287.4  821.86
   404.8  829.93   451.6  829.91   470.4  828.15     499  813.12   505.9  811.71
   508.5  811.18   520.9  811.59   566.1  823.02   585.2  832.03   633.5   880.2
   672.3  913.43   701.4  931.05   749.9  966.89   759.6  972.15   769.3  974.48
   788.7  974.15   817.8  986.07   837.2  987.04   856.6  998.07     876  999.96
#Mann= 3 , 0 , 0
       0      .1       0   505.9    .045       0   520.9      .1       0
Bank Sta=505.9,520.9
XS Rating Curve= 0 ,0
Exp/Cntr=0.3,0.1

Type RM Length L Ch R = 1 ,1878.2  ,272.3,260.2,249.1
XS GIS Cut Line= 4
     1834273.617      430917.255     1834049.658      430840.866
      1833856.95      430773.158     1833389.936      430729.755
#Sta/Elev= 30
       0  930.07    19.7  926.17    29.6  922.35    39.4  916.83      69  887.32
    78.9  881.36    98.6  873.43   128.2  858.49   167.6  844.09   197.2  827.48
   216.9  818.89   236.6  812.74   304.7  812.48   314.4  810.62   324.2  807.37
   333.8   807.2  335.26  807.48   343.6  809.07   363.1  817.89   421.4  828.15
   450.9  840.66   520.7  857.15   600.6  885.65   630.5  893.07   670.4  909.67
   690.4  916.55   790.2  933.32   820.1  937.23     860  951.56   909.9  954.91
#Mann= 3 , 0 , 0
       0     .07       0   314.4    .045       0  335.26      .1       0
Bank Sta=314.4,335.26
XS Rating Curve= 0 ,0
Exp/Cntr=0.3,0.1

Type RM Length L Ch R = 1 ,1618    ,736.3,764.7,792.7
XS GIS Cut Line= 4
     1834275.279      430527.317     1834012.692      430544.678
     1833804.358       430588.08     1833383.352      430633.653
#Sta/Elev= 30
       0  910.52     9.8  909.18    29.2  901.79    97.5  868.23   107.2  865.19
   136.4  860.68   146.2  856.67   204.7  824.97   272.8   811.6   321.2  810.34
   340.5  807.59  349.83  804.65   359.9  804.44  362.66  804.63   388.9  807.56
   427.6   807.7   437.3  809.83   466.3  824.93   505.5  843.12   544.9  871.33
   554.8  874.93   584.3  877.35   594.1  882.87   613.8   897.9   643.4  911.01
   761.6   937.9   791.1  946.34     860  950.01   879.7  953.03   899.4  958.23
#Mann= 3 , 0 , 0
       0     .08       0  349.83    .045       0  362.66      .1       0
Bank Sta=349.83,362.66
XS Rating Curve= 0 ,0
Exp/Cntr=0.3,0.1

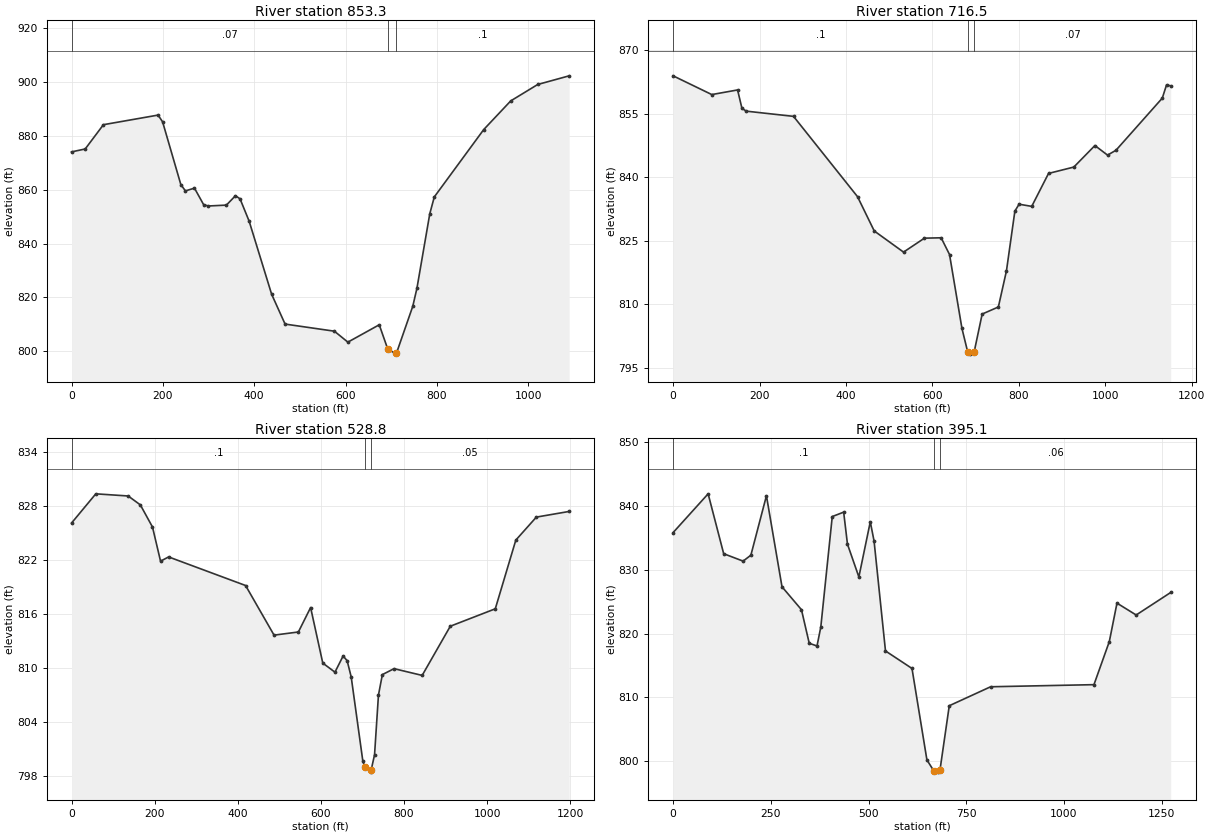
Type RM Length L Ch R = 1 ,853.3   ,139,136.8,133.7
XS GIS Cut Line= 5
      1834184.74       430425.58     1833906.963      430139.303
     1833697.841      429960.802      1833645.41      429874.691
     1833395.135      429683.284
#Sta/Elev= 30
       0  874.03    29.9  875.11    69.8  884.13   189.5   887.7   199.4  885.19
   239.3  861.91   249.3  859.54   269.2  860.56   289.2  854.44   299.2  853.93
   339.1  854.26     359  857.76     369  856.58   388.9   848.3   438.2  821.13
   467.6  810.07   575.6  807.43   605.1  803.36   673.8  809.81   692.2   800.9
   710.5  798.91   711.5  799.25   747.2  816.66   756.3  823.32   784.5  851.06
   794.4  857.31   902.6  882.32   961.7  892.96  1020.8  899.06  1089.7  902.28
#Mann= 3 , 0 , 0
       0     .07       0   692.2    .045       0   711.5      .1       0
Bank Sta=692.2,711.5
XS Rating Curve= 0 ,0
Exp/Cntr=0.3,0.1

Type RM Length L Ch R = 1 ,716.5   ,188.3,187.7,187.9
XS GIS Cut Line= 5
     1834274.801      430358.306     1833995.504      430088.956
     1833812.345      429889.303     1833735.471      429807.416
      1833420.54      429594.526
#Sta/Elev= 30
       0  863.92    89.5   859.5   149.2  860.59   159.2  856.28   169.1  855.59
   278.6  854.36   426.7  835.42   465.4  827.33   533.2  822.34   581.5  825.63
   620.2  825.72   639.6  821.77   668.3  804.36   681.5  798.84     687  798.28
   696.5  798.75   715.1  807.73   752.6   809.4   771.3  817.91   790.8  832.01
   800.5  833.64   829.8  833.13   868.7   840.9   927.2   842.4     976  847.48
  1005.2  845.22  1024.7  846.36  1131.9  858.66  1141.7  861.77  1151.4  861.55
#Mann= 3 , 0 , 0
       0      .1       0   681.5    .045       0   696.5     .07       0
Bank Sta=681.5,696.5
XS Rating Curve= 0 ,0
Exp/Cntr=0.3,0.1

Type RM Length L Ch R = 1 ,528.8   ,138.3,133.8,130
XS GIS Cut Line= 6
     1834400.669      430212.907     1834133.431      429956.939
      1833913.77      429748.128     1833851.313       429666.14
     1833725.445       429576.08      1833493.24      429444.786
#Sta/Elev= 30
       0  826.12    58.4  829.37   136.3  829.13   165.6  828.14   194.8  825.68
   214.2  821.88   233.7  822.35   418.9  819.17   487.4  813.65     546     814
   575.4  816.72   604.7  810.54     634  809.53   653.6  811.33   663.3  810.81
   673.1     809   701.2   799.6   706.2  798.99     720  798.41   721.2  798.66
   729.3  800.34   738.7  806.98   748.1  809.26   776.2  809.92   843.9  809.17
   911.6  814.64  1019.9  816.58  1069.3  824.22  1118.7  826.78  1197.7  827.41
#Mann= 3 , 0 , 0
       0      .1       0   706.2    .045       0   721.2     .05       0
Bank Sta=706.2,721.2
XS Rating Curve= 0 ,0
Exp/Cntr=0.3,0.1

Type RM Length L Ch R = 1 ,395.1   ,381.5,395.1,407.6
XS GIS Cut Line= 6
     1834454.272      430143.817     1834212.858      429865.793
      1834059.74      429702.411      1833930.74      429574.995
     1833801.928      429505.796     1833476.407      429367.776
#Sta/Elev= 30
       0  835.81    89.6  841.88   129.4   832.5   179.1  831.34     199  832.27
   238.8  841.58   278.6  827.32   328.4  823.73   348.3  818.47   368.2  818.05
   377.9  821.02   407.2  838.32   436.4  839.01   446.1     834   475.3  828.86
   504.5   837.5   514.2  834.48   543.4  817.27   611.2  814.53   649.4   800.2
     668  798.39     678  798.29     683  798.69   706.6  808.69   812.4  811.66
  1076.8  811.99  1116.1  818.74  1135.7  824.76  1184.8   822.9  1273.2  826.43
#Mann= 3 , 0 , 0
       0      .1       0     668    .045       0     683     .06       0
Bank Sta=668,683
XS Rating Curve= 0 ,0
Exp/Cntr=0.3,0.1

Chan Stop Cuts=-1
Use User Specified Reach Order=0
Composite Channel Slope=5